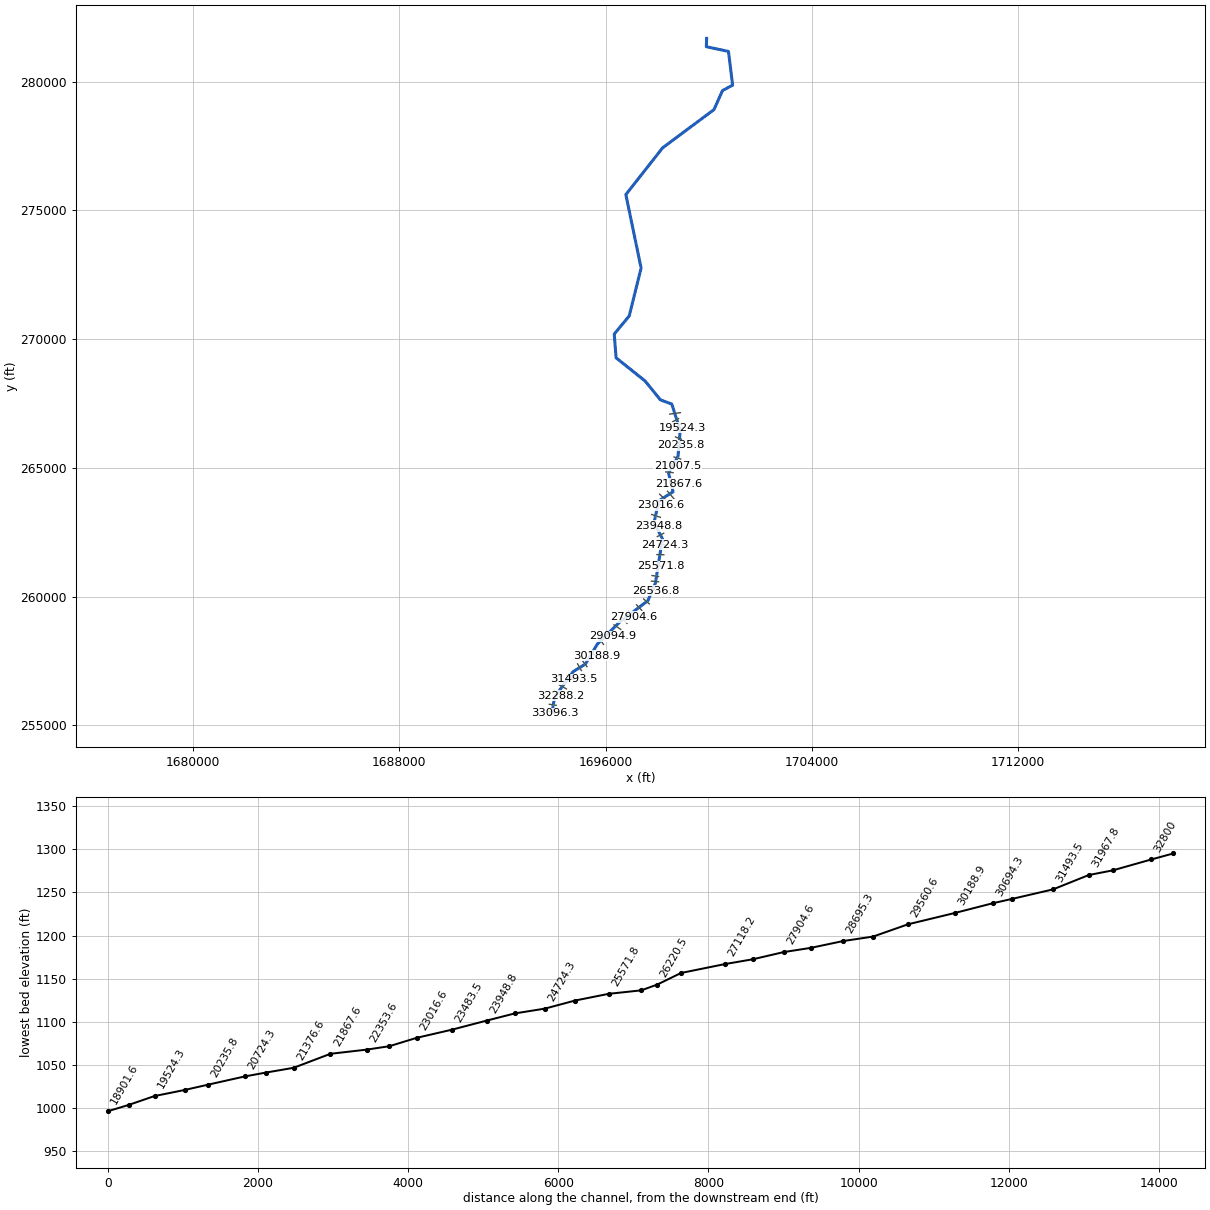
--- RICHCRK.prj (project) ---

Proj Title=RICHCRK
Current Plan=p01
Default Exp/Contr=0,0
English Units
Geom File=g01
Flow File=f01
Plan File=p01
BEGIN DESCRIPTION:
END DESCRIPTION:
DSS Export Rating Curves= 0
DSS Export Rating Curve Sorted= 0
DSS Export Volume Flow Curves= 0
DXF OffsetX= 0
DXF OffsetY= 0
DXF ScaleX= 0
DXF ScaleY= 0

--- RICHCRK.p01 (plan) ---

Plan Title=Floodplain
Program Version=4.00
Geom File=g01
Flow File=f01
K Sum by GR=0
Std Step Tol=0.01
Critical Tol=0.01
Num of Std Step Trials=20
Max Error Tol=0.3
Flow Tol Ratio=0.001
Split Flow NTrial=30
Split Flow Tol=0.02
Split Flow Ratio=0.02
Log Output Level=0
Friction Slope Method=1
Unsteady Friction Slope Method=2
Unsteady Bridges Friction Slope Method=1
Global Log Level=0
CheckData=False
Run HTab=0
Run UNet=0
Run PostProcess=0
UNET Theta=0
UNET Theta Warmup=0
UNET ZTol=0
UNET ZSATol=0
UNET MxIter=0
UNET MaxInSteps=0
UNET DtIC=0
UNET DtMin=0
UNET MaxCRTS=0
UNET WFStab=0
UNET SFStab=0
UNET WFX=0
UNET SFX=0
UNET DSS MLevel=0
UNET DZMax Abort=0
UNET Convert EG Bridges=0
UNET Use Existing IB Tables=0
UNET Froude Limit=0
UNET Froude Power=0
Write IC File=0
Echo Input=False
Echo Output=False
Write Detailed=0

--- RICHCRK.f01 (steady flow) ---

Flow Title=NFF Regression Equation
Program Version=4.00
Number of Profiles=1
Profile Names=P100yr
River Rch & RM=RICHCRK,Main      ,33096.3
953.4482
River Rch & RM=RICHCRK,Main      ,30188.9
1013.337
River Rch & RM=RICHCRK,Main      ,27904.6
1173.221
River Rch & RM=RICHCRK,Main      ,26536.8
1300.843
River Rch & RM=RICHCRK,Main      ,24724.3
1357.539
River Rch & RM=RICHCRK,Main      ,24324.3
1362.415
River Rch & RM=RICHCRK,Main      ,18329.3
1735.756
River Rch & RM=RICHCRK,Main      ,16018.6
1846.716
River Rch & RM=RICHCRK,Main      ,15177.7
2015.450
River Rch & RM=RICHCRK,Main      ,13124.3
2055.566
River Rch & RM=RICHCRK,Main      ,7098.9
2463.798
River Rch & RM=RICHCRK,Main      ,3147.9
2584.903
River Rch & RM=RICHCRK,Main      ,2747.9
2921.206
River Rch & RM=RICHCRK,Main      ,291.6
2954.798
Boundary for River Rch & Prof#=RICHCRK,Main      ,1
Up Type=0
Dn Type=3
Dn Slope=0.008146

--- RICHCRK.g01 (geometry) ---

Geom Title=USGS 10m DEM
Program Version=4.10

River Reach=RICHCRK         ,Main
Reach XY= 30
     1693918.899      255494.479     1694026.612      256101.378
     1694745.856      257085.851     1695215.768      257375.257
     1695686.317      258159.505     1696551.495      259011.943
     1697641.311      259840.143     1697932.073      260517.607
     1698205.409      262247.962     1697879.954      262860.651
     1698060.633      263713.089     1698617.729      264069.816
      1698442.84        264801.8     1698809.991      265442.286
     1698893.381      266444.132     1698570.242      267473.774
     1698126.651      267638.239     1697532.493       268372.54
     1696407.877      269271.306     1696336.069      270194.394
     1696916.328      270895.106     1697378.452      272757.497
      1696786.61      275610.152     1698212.358      277426.214
     1700205.625       278911.03     1700533.397      279647.648
     1700927.186      279860.757     1700766.439      281170.086
     1699908.211      281353.082     1699919.793      281678.537

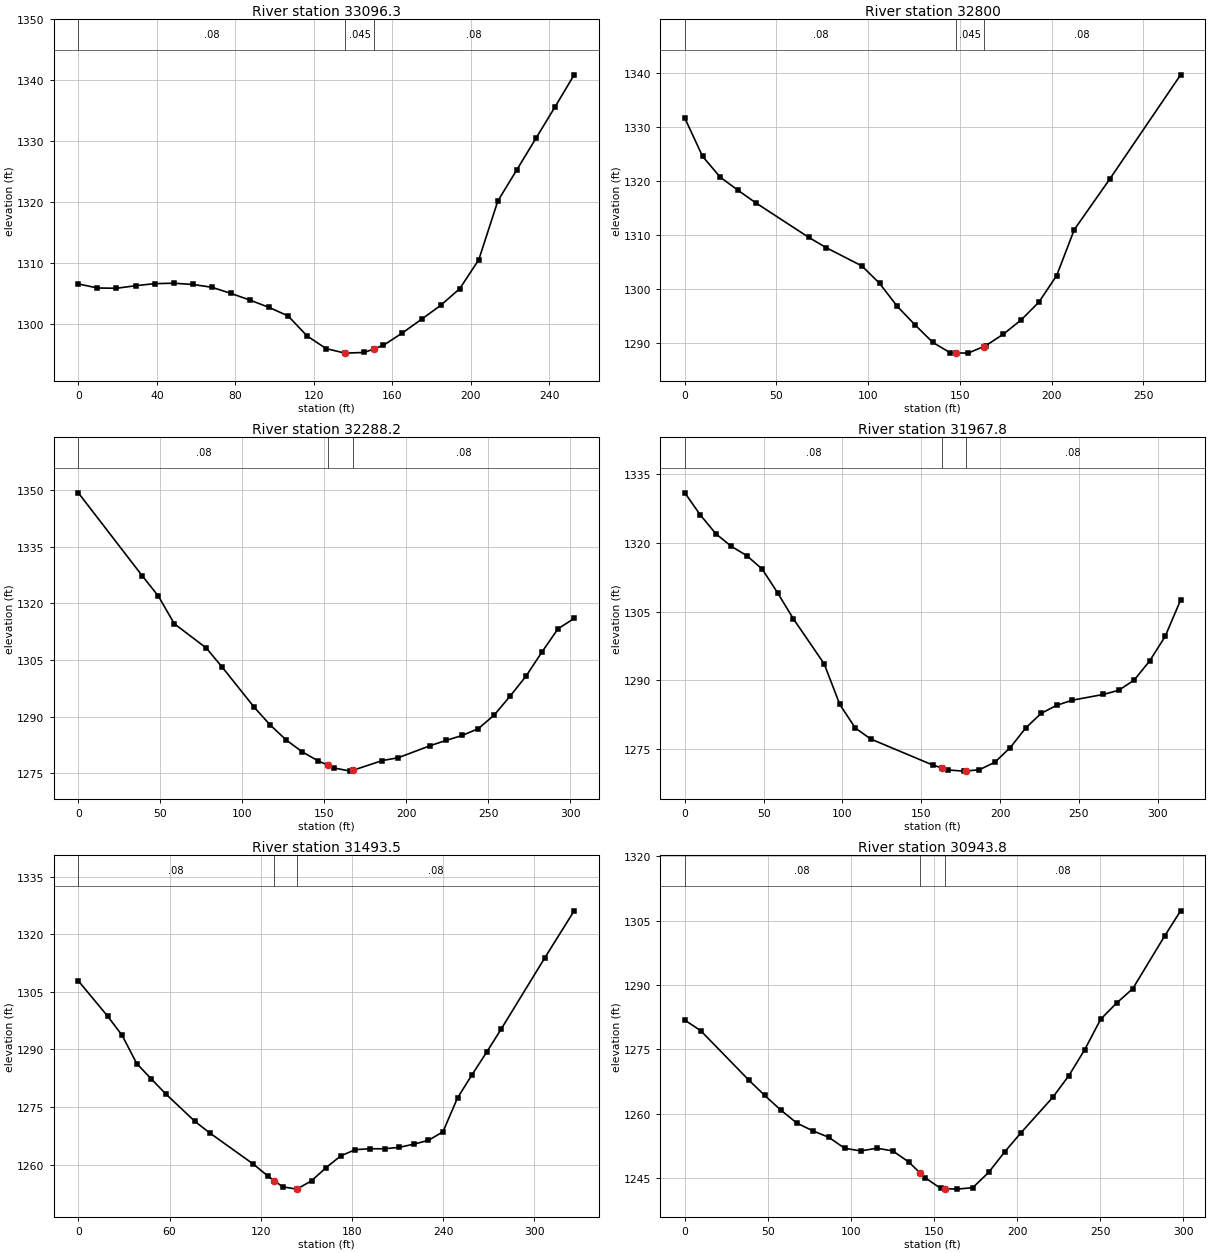
Type RM Length L Ch R = 1 ,33096.3 ,291.2,296.3,301.4
XS GIS Cut Line= 2
      1693790.38      255556.103     1694025.275       255462.98
#Sta/Elev= 28
       0 1306.62     9.7 1305.96    19.4 1305.91    29.2 1306.33    38.9 1306.67
    48.6 1306.74    58.3 1306.54      68 1306.08    77.8 1305.07    87.5 1303.97
    97.2 1302.77   106.9 1301.38   116.6 1298.09   126.3 1296.02   135.9 1295.28
   145.8 1295.39   150.9 1296.01   155.5 1296.56   165.2  1298.6   174.9 1300.83
   184.6 1303.09   194.4 1305.85   204.1  1310.6   213.8 1320.22   223.5 1325.34
   233.2 1330.48     243 1335.67   252.7  1340.9
#Mann= 3 , 0 , 0
       0     .08       0   135.9    .045       0   150.9     .08       0
Bank Sta=135.9,150.9
XS Rating Curve= 0 ,0
Exp/Cntr=0.3,0.1

Type RM Length L Ch R = 1 ,32800   ,523.8,511.7,499.6
XS GIS Cut Line= 2
     1693819.257      255816.959     1694086.552       255776.17
#Sta/Elev= 24
       0 1331.64     9.7 1324.56    19.3 1320.73      29  1318.3    38.6    1316
    67.6  1309.6    77.2 1307.68    96.6 1304.32   106.2 1301.11   115.9 1296.85
   125.5 1293.46   135.2 1290.21   144.8 1288.28   147.9 1288.26   154.5 1288.22
   162.9 1289.42   164.2 1289.61   173.8 1291.74   183.5 1294.37   193.1 1297.64
   202.8 1302.54   212.4 1311.03   231.8 1320.39   270.4 1339.62
#Mann= 3 , 0 , 0
       0     .08       0   147.9    .045       0   162.9     .08       0
Bank Sta=147.9,162.9
XS Rating Curve= 0 ,0
Exp/Cntr=0.3,0.1

Type RM Length L Ch R = 1 ,32288.2 ,316.1,320.3,325.4
XS GIS Cut Line= 2
     1694033.352      256347.404     1694262.737      256150.538
#Sta/Elev= 27
       0 1349.26      39 1327.28    48.8 1321.93    58.5 1314.62      78 1308.19
    87.8 1303.08   107.3 1292.48     117 1287.81   126.8 1283.83   136.5 1280.71
   146.3  1278.3   152.4 1277.13     156 1276.44   165.8 1275.61   167.4 1275.83
   185.3  1278.4     195 1279.15   214.5 1282.34   224.3 1283.75     234 1285.04
   243.8 1286.84   253.5 1290.42   263.3 1295.48     273 1300.77   282.8 1307.22
   292.5  1313.3   302.3 1316.02
#Mann= 3 , 0 , 0
       0     .08       0   152.4    .045       0   167.4     .08       0
Bank Sta=152.4,167.4
XS Rating Curve= 0 ,0
Exp/Cntr=0.3,0.1

Type RM Length L Ch R = 1 ,31967.8 ,474,474.2,473.5
XS GIS Cut Line= 2
      1694206.29      256567.816     1694480.472       256413.77
#Sta/Elev= 30
       0  1330.9     9.8 1326.09    19.7 1321.97    29.5 1319.23    39.3  1317.2
    49.1 1314.26      59 1309.01    68.8 1303.45    88.4  1293.6    98.3 1284.75
   108.1 1279.61   117.9  1277.2   157.2 1271.53   163.3 1270.86   167.1 1270.44
   176.9 1270.19   178.3 1270.23   186.7 1270.47   196.6 1272.11   206.4 1275.31
   216.2 1279.59     226 1282.79   235.9 1284.54   245.7 1285.66   265.4 1286.91
   275.2 1287.82     285 1290.04   294.8  1294.2   304.7 1299.58   314.5 1307.53
#Mann= 3 , 0 , 0
       0     .08       0   163.3    .045       0   178.3     .08       0
Bank Sta=163.3,178.3
XS Rating Curve= 0 ,0
Exp/Cntr=0.3,0.1

Type RM Length L Ch R = 1 ,31493.5 ,562.2,549.6,536.9
XS GIS Cut Line= 2
     1694497.483      256936.034     1694784.614      256781.464
#Sta/Elev= 29
       0 1307.87    19.2  1298.7    28.8 1293.67    38.4 1286.32      48 1282.29
    57.6 1278.37    76.7 1271.23    86.3 1268.27   115.1 1260.11   124.7 1256.98
   128.7 1255.82   134.3  1254.2   143.7 1253.59   153.4 1255.77     163 1259.21
   172.6 1262.25   182.2 1263.88   191.8  1264.1   201.4 1264.11     211 1264.48
   220.6  1265.3   230.2  1266.3   239.8 1268.52   249.4 1277.38     259 1283.44
   268.6 1289.32   278.1  1295.3   306.9 1313.94   326.1 1326.12
#Mann= 3 , 0 , 0
       0     .08       0   128.7    .045       0   143.7     .08       0
Bank Sta=128.7,143.7
XS Rating Curve= 0 ,0
Exp/Cntr=0.3,0.1

Type RM Length L Ch R = 1 ,30943.8 ,246.5,249.4,252.4
XS GIS Cut Line= 2
     1694913.839      257385.196     1695061.096       257125.74
#Sta/Elev= 30
       0 1281.84     9.6 1279.37    38.5 1267.87    48.1 1264.28    57.7  1260.9
    67.4 1257.85      77 1256.04    86.6 1254.54    96.2 1251.96   105.9 1251.36
   115.5 1251.98   125.1 1251.37   134.7 1248.78   141.3 1246.32   144.4 1245.16
     154 1242.61   156.3 1242.57   163.6 1242.45   173.2 1242.78   182.8 1246.35
   192.5 1251.15   202.1 1255.52   221.3 1263.81     231 1268.86   240.6 1274.96
   250.2 1282.05   259.8 1285.83   269.5 1289.17   288.7 1301.46   298.3 1307.32
#Mann= 3 , 0 , 0
       0     .08       0   141.3    .045       0   156.3     .08       0
Bank Sta=141.3,156.3
XS Rating Curve= 0 ,0
Exp/Cntr=0.3,0.1

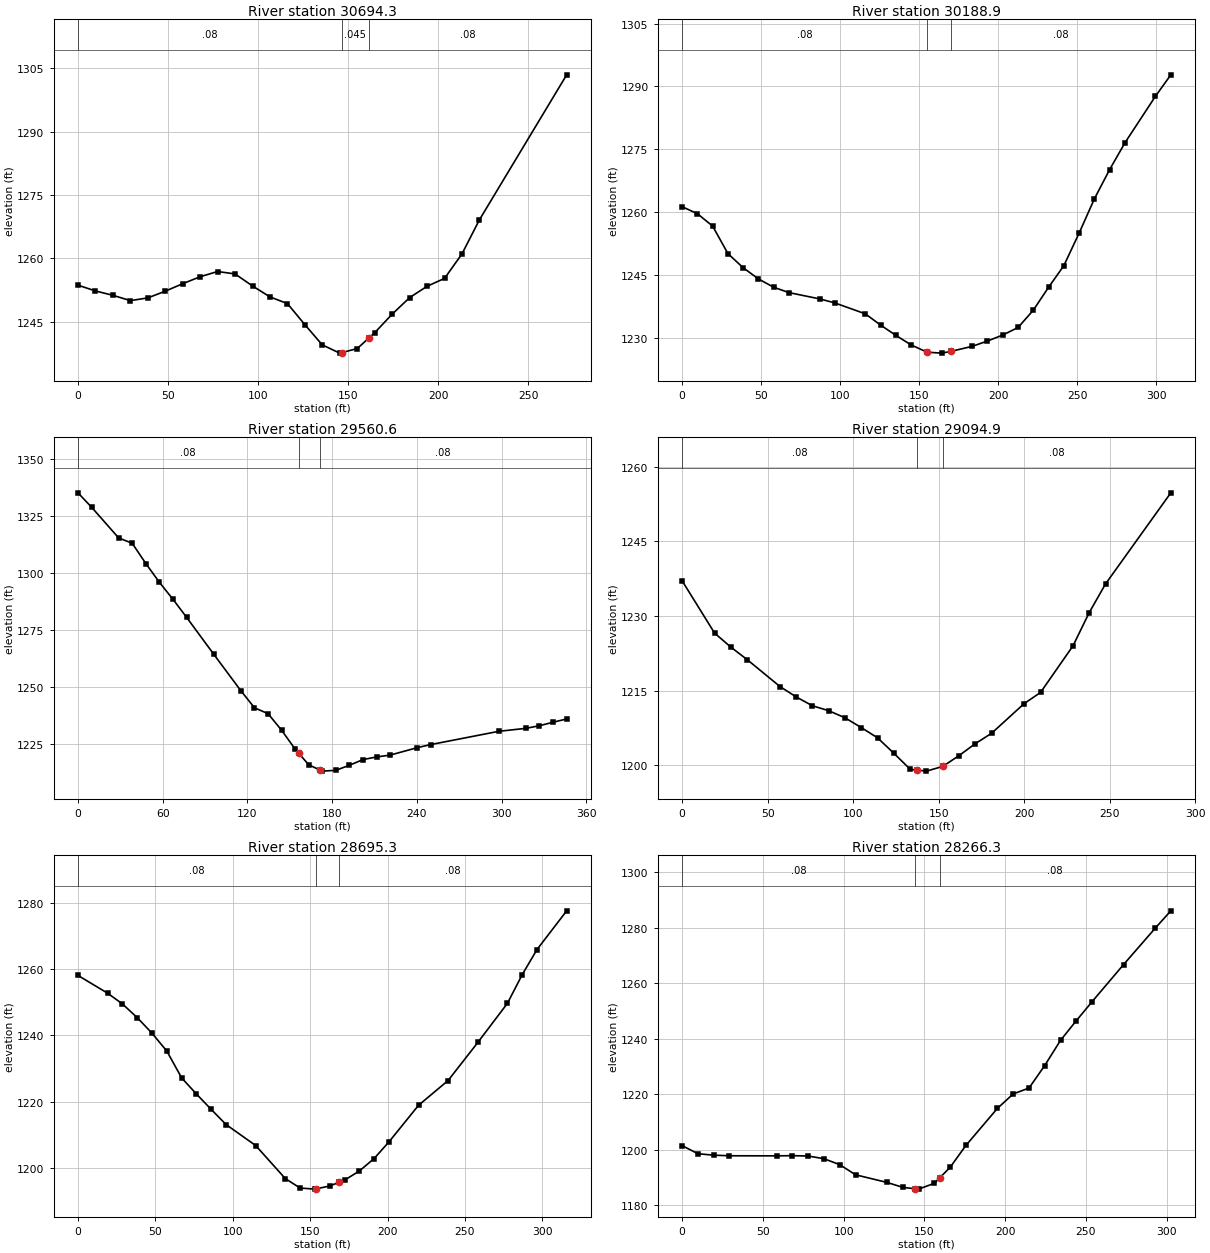
Type RM Length L Ch R = 1 ,30694.3 ,494.9,505.3,515.6
XS GIS Cut Line= 2
     1695114.952      257492.676     1695278.646      257276.352
#Sta/Elev= 27
       0 1253.65     9.7 1252.28    19.4 1251.25    29.1 1249.99    38.8 1250.64
    48.4 1252.22    58.1 1253.99    67.8 1255.64    77.5 1256.88    87.2 1256.31
    96.9 1253.46   106.6 1250.87   116.3 1249.28     126 1244.28   135.6 1239.53
   145.3 1237.57   146.4 1237.69     155 1238.64   161.4 1241.11   164.7 1242.39
   174.4 1246.78   184.1  1250.7   193.8 1253.39   203.5 1255.25   213.2 1261.07
   222.8 1269.07   271.3 1303.42
#Mann= 3 , 0 , 0
       0     .08       0   146.4    .045       0   161.4     .08       0
Bank Sta=146.4,161.4
XS Rating Curve= 0 ,0
Exp/Cntr=0.3,0.1

Type RM Length L Ch R = 1 ,30188.9 ,639.8,628.1,616.3
XS GIS Cut Line= 2
     1695379.453      257833.608     1695655.595      257694.559
#Sta/Elev= 30
       0 1261.27     9.7 1259.58    19.3 1256.63      29 1250.05    38.6 1246.69
    48.3    1244      58 1242.01    67.6 1240.74      87 1239.24    96.6 1238.28
   115.9 1235.67   125.6 1232.97   135.3 1230.51   144.9 1228.24     155  1226.5
   164.2 1226.28     170 1226.69   183.6 1227.91   193.2 1229.17   202.9 1230.61
   212.6 1232.42   222.2 1236.54   231.9 1242.04   241.5 1247.17   251.2 1254.97
   260.9 1263.19   270.5 1270.14   280.2 1276.55   299.5 1287.66   309.2 1292.77
#Mann= 3 , 0 , 0
       0     .08       0     155    .045       0     170     .08       0
Bank Sta=155,170
XS Rating Curve= 0 ,0
Exp/Cntr=0.3,0.1

Type RM Length L Ch R = 1 ,29560.6 ,459.1,465.4,471.7
XS GIS Cut Line= 2
     1695726.607      258428.753     1695919.052      258141.142
#Sta/Elev= 30
       0 1335.27     9.6 1328.98    28.8 1315.47    38.4 1313.12    48.1 1304.18
    57.7 1295.94    67.3 1288.49    76.9 1280.62    96.1 1264.43   115.4 1248.33
     125 1240.88   134.6 1238.29   144.2 1231.03   153.8 1222.72   156.2    1221
   163.4 1215.85   171.2 1213.58     173 1213.06   182.6 1213.41   192.2 1215.63
   201.9 1218.14   211.5 1219.29   221.1  1220.1   240.3 1223.37   249.9 1224.73
     298 1230.54   317.2 1231.85   326.8 1232.99   336.4 1234.53   346.1 1235.96
#Mann= 3 , 0 , 0
       0     .08       0   156.2    .045       0   171.2     .08       0
Bank Sta=156.2,171.2
XS Rating Curve= 0 ,0
Exp/Cntr=0.3,0.1

Type RM Length L Ch R = 1 ,29094.9 ,397.4,399.7,402
XS GIS Cut Line= 2
      1696061.32      258639.434     1696282.082      258457.997
#Sta/Elev= 25
       0 1237.06      19 1226.54    28.6  1223.7    38.1  1221.2    57.2 1215.81
    66.7 1213.72    76.2 1211.94    85.7 1210.95    95.2 1209.53   104.8 1207.55
   114.3 1205.49   123.8  1202.4   133.4 1199.17   137.5 1199.01   142.9  1198.8
   152.5 1199.76   161.9 1201.91   171.4 1204.31     181 1206.41     200 1212.37
   209.6 1214.61   228.6 1223.99   238.1 1230.68   247.6 1236.42   285.8 1254.74
#Mann= 3 , 0 , 0
       0     .08       0   137.5    .045       0   152.5     .08       0
Bank Sta=137.5,152.5
XS Rating Curve= 0 ,0
Exp/Cntr=0.3,0.1

Type RM Length L Ch R = 1 ,28695.3 ,435.8,428.9,421.7
XS GIS Cut Line= 2
     1696324.627      258900.666     1696587.737      258726.265
#Sta/Elev= 28
       0  1258.1    19.1 1252.76    28.7 1249.51    38.3 1245.35    47.8 1240.68
    57.4 1235.27      67 1227.16    76.5 1222.33    86.1 1217.65    95.7 1213.09
   114.8 1206.77   133.9 1196.81   143.5 1193.94     153 1193.61   153.6 1193.67
   162.6 1194.55   168.6 1195.66   172.2 1196.32   181.7 1199.06   191.3 1202.84
   200.9 1207.87     220 1218.91   239.1 1226.39   258.3 1237.88   277.4 1249.67
     287 1258.36   296.5  1265.9   315.7  1277.6
#Mann= 3 , 0 , 0
       0     .08       0   153.6    .045       0   168.6     .08       0
Bank Sta=153.6,168.6
XS Rating Curve= 0 ,0
Exp/Cntr=0.3,0.1

Type RM Length L Ch R = 1 ,28266.3 ,359.5,361.6,363.7
XS GIS Cut Line= 2
     1696628.856      259185.579       1696829.6      258959.137
#Sta/Elev= 28
       0 1201.41     9.8 1198.49    19.5 1197.97    29.3 1197.75    58.6 1197.72
    68.3 1197.79    78.1 1197.66    87.8 1196.69    97.6 1194.55   107.4 1190.89
   126.9 1188.13   136.7 1186.35   144.4 1185.85   146.4 1185.72   156.2 1187.82
   159.4 1189.72     166 1193.63   175.7 1201.46   195.2 1214.83     205 1220.06
   214.8 1222.18   224.5 1230.28   234.3 1239.38     244 1246.42   253.8  1253.3
   273.3 1266.69   292.8 1279.74   302.6  1286.1
#Mann= 3 , 0 , 0
       0     .08       0   144.4    .045       0   159.4     .08       0
Bank Sta=144.4,159.4
XS Rating Curve= 0 ,0
Exp/Cntr=0.3,0.1

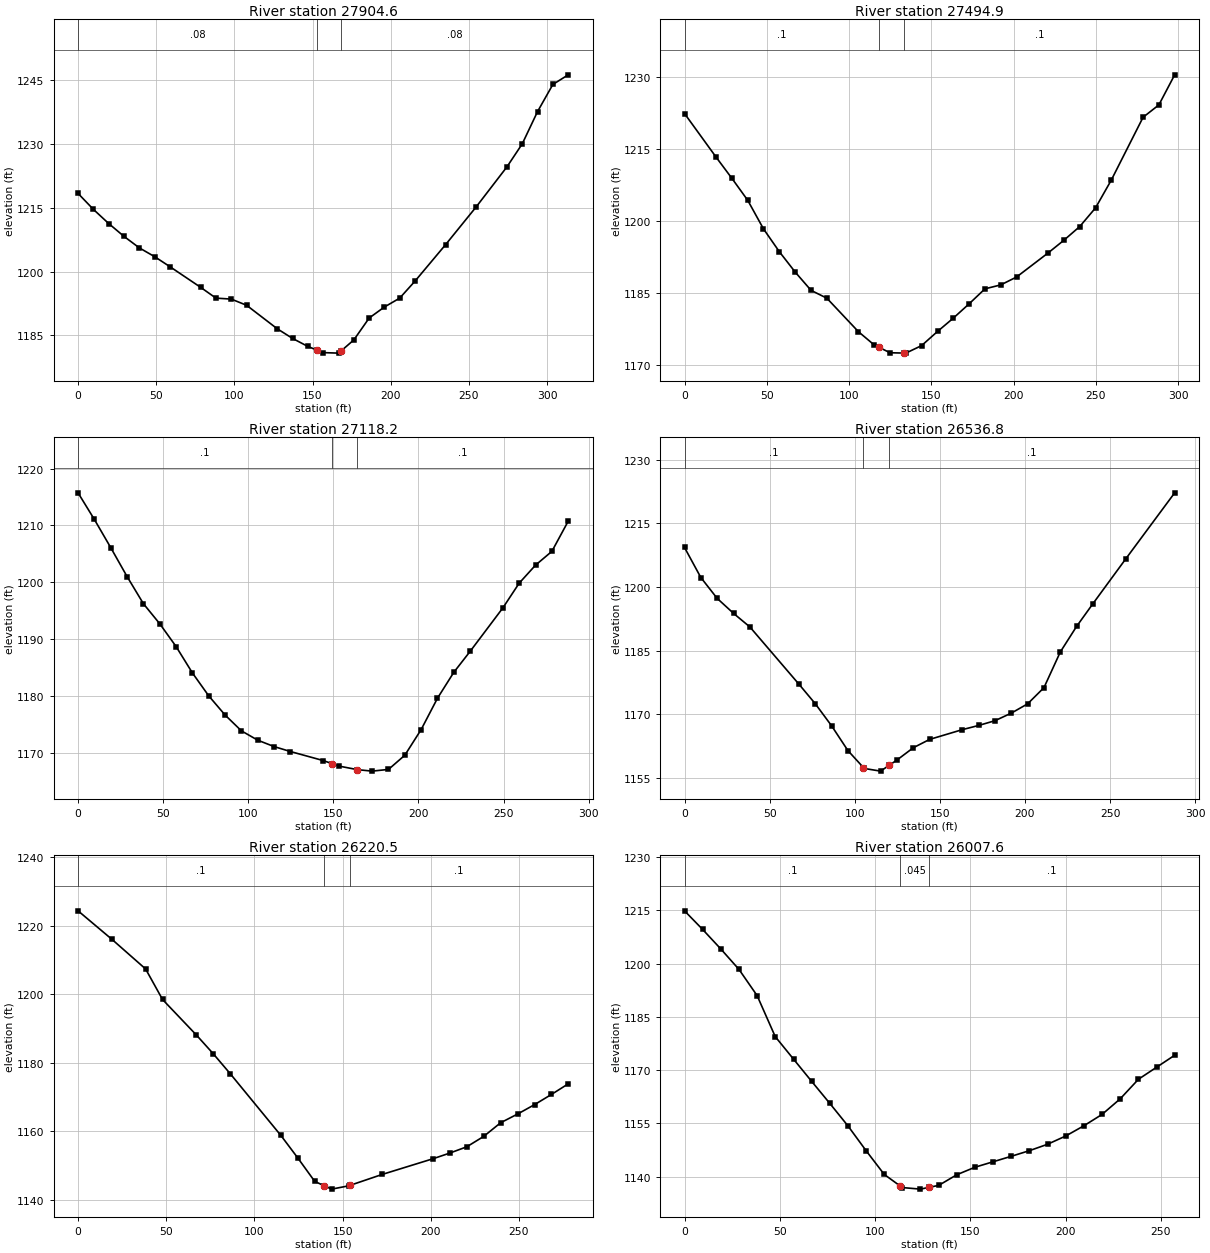
Type RM Length L Ch R = 1 ,27904.6 ,411.2,409.6,408
XS GIS Cut Line= 2
     1696883.741      259420.136     1697111.994       259205.22
#Sta/Elev= 30
       0  1218.4     9.8 1214.65    19.6 1211.32    29.4 1208.29    39.2 1205.59
      49 1203.52    58.8 1201.16    78.4 1196.31    88.2 1193.77      98 1193.54
   107.8 1192.09   127.4 1186.56   137.2 1184.29     147  1182.4     153 1181.51
   156.8 1180.95   166.6 1180.83     168 1181.27   176.4 1183.94   186.2 1189.09
   195.9 1191.67   205.7 1193.76   215.5 1197.76   235.1 1206.36   254.7 1215.26
   274.3 1224.64   284.1 1230.06   293.9 1237.66   303.7 1244.04   313.5  1246.3
#Mann= 3 , 0 , 0
       0     .08       0     153    .045       0     168     .08       0
Bank Sta=153,168
XS Rating Curve= 0 ,0
Exp/Cntr=0.3,0.1

Type RM Length L Ch R = 1 ,27494.9 ,374.3,376.7,379.1
XS GIS Cut Line= 2
     1697201.578      259680.185     1697405.212      259462.767
#Sta/Elev= 30
       0 1222.48    19.2 1213.38    28.8 1208.96    38.4 1204.39      48 1198.42
    57.7 1193.63    67.3  1189.4    76.9  1185.6    86.5 1183.97   105.7 1176.98
   115.3 1174.21   118.4 1173.69   124.9 1172.59   133.4 1172.52   134.5 1172.51
   144.1 1174.08   153.8 1177.04   163.4 1179.82     173  1182.8   182.6 1185.92
   192.2 1186.74   201.8 1188.38     221 1193.41   230.6 1196.06   240.2 1198.91
   249.8  1202.8   259.4 1208.61   278.7  1221.7   288.3 1224.28   297.9 1230.55
#Mann= 3 , 0 , 0
       0      .1       0   118.4    .045       0   133.4      .1       0
Bank Sta=118.4,133.4
XS Rating Curve= 0 ,0
Exp/Cntr=0.3,0.1

Type RM Length L Ch R = 1 ,27118.2 ,576.3,581.2,586.1
XS GIS Cut Line= 2
     1697476.636      259905.232     1697694.618      259716.975
#Sta/Elev= 30
       0 1215.73     9.6 1211.05    19.2 1206.11    28.8 1201.03    38.4 1196.26
      48 1192.74    57.6 1188.74    67.2  1184.1    76.8 1180.07    86.4 1176.71
      96 1173.93   105.6 1172.29   115.2 1171.17   124.8  1170.3     144 1168.72
   149.1 1168.19   153.6 1167.73   164.1 1167.12   172.8 1166.86   182.4 1167.16
     192 1169.65   201.6 1174.16   211.2 1179.67   220.8 1184.22   230.4  1187.9
   249.6 1195.52   259.2 1199.87   268.8 1203.03   278.4 1205.45     288 1210.75
#Mann= 3 , 0 , 0
       0      .1       0   149.1    .045       0   164.1      .1       0
Bank Sta=149.1,164.1
XS Rating Curve= 0 ,0
Exp/Cntr=0.3,0.1

Type RM Length L Ch R = 1 ,26536.8 ,306.7,316.2,325.7
XS GIS Cut Line= 2
     1697691.467      260372.793     1697943.194      260232.827
#Sta/Elev= 27
       0 1209.32     9.6 1202.23    19.2 1197.31    28.8 1193.78    38.4 1190.58
    67.2 1177.09    76.8 1172.48    86.4 1167.27      96 1161.42   105.1 1157.42
   105.6  1157.2   115.2 1156.57   120.1  1157.9   124.8 1159.18   134.4 1162.08
     144 1164.05   163.2 1166.35   172.8 1167.34   182.4 1168.46     192 1170.25
   201.6 1172.44   211.2 1176.26   220.8 1184.67   230.4 1190.72     240 1196.08
   259.2  1206.6     288 1222.21
#Mann= 3 , 0 , 0
       0      .1       0   105.1    .045       0   120.1      .1       0
Bank Sta=105.1,120.1
XS Rating Curve= 0 ,0
Exp/Cntr=0.3,0.1

Type RM Length L Ch R = 1 ,26220.5 ,214.2,212.8,211.4
XS GIS Cut Line= 2
     1697778.952      260599.104      1698055.77      260574.179
#Sta/Elev= 24
       0 1224.41    19.2 1216.09    38.3 1207.44    47.9 1198.53    67.1 1188.15
    76.7 1182.66    86.3 1176.85     115 1158.84   124.6 1152.26   134.2 1145.42
   139.3 1144.22   143.8 1143.17   153.4 1144.13   154.3 1144.29   172.5 1147.47
   201.3 1152.05   210.8  1153.7   220.4 1155.53     230 1158.56   239.6 1162.55
   249.2 1165.09   258.8 1167.83   268.4 1170.81   277.9  1173.9
#Mann= 3 , 0 , 0
       0      .1       0   139.3    .045       0   154.3      .1       0
Bank Sta=139.3,154.3
XS Rating Curve= 0 ,0
Exp/Cntr=0.3,0.1

Type RM Length L Ch R = 1 ,26007.6 ,436.4,436,435.6
XS GIS Cut Line= 2
     1697801.462      260816.787      1698055.77      260778.256
#Sta/Elev= 30
       0 1214.87     9.5 1209.63      19 1204.15    28.6 1198.35    38.1 1190.98
    47.6 1179.43    57.2 1173.09    66.7 1166.83    76.2 1160.64    85.7 1154.32
    95.3 1147.28   104.8  1140.6   113.2 1137.33   114.3  1136.9   123.8 1136.46
   128.2 1136.95   133.4 1137.52   142.9 1140.52   152.4 1142.63     162 1144.18
   171.5 1145.72     181  1147.3   190.5  1149.1     200 1151.42   209.6 1154.32
   219.1 1157.51   228.6 1161.89   238.2 1167.42   247.7  1170.8   257.2 1174.18
#Mann= 3 , 0 , 0
       0      .1       0   113.2    .045       0   128.2      .1       0
Bank Sta=113.2,128.2
XS Rating Curve= 0 ,0
Exp/Cntr=0.3,0.1

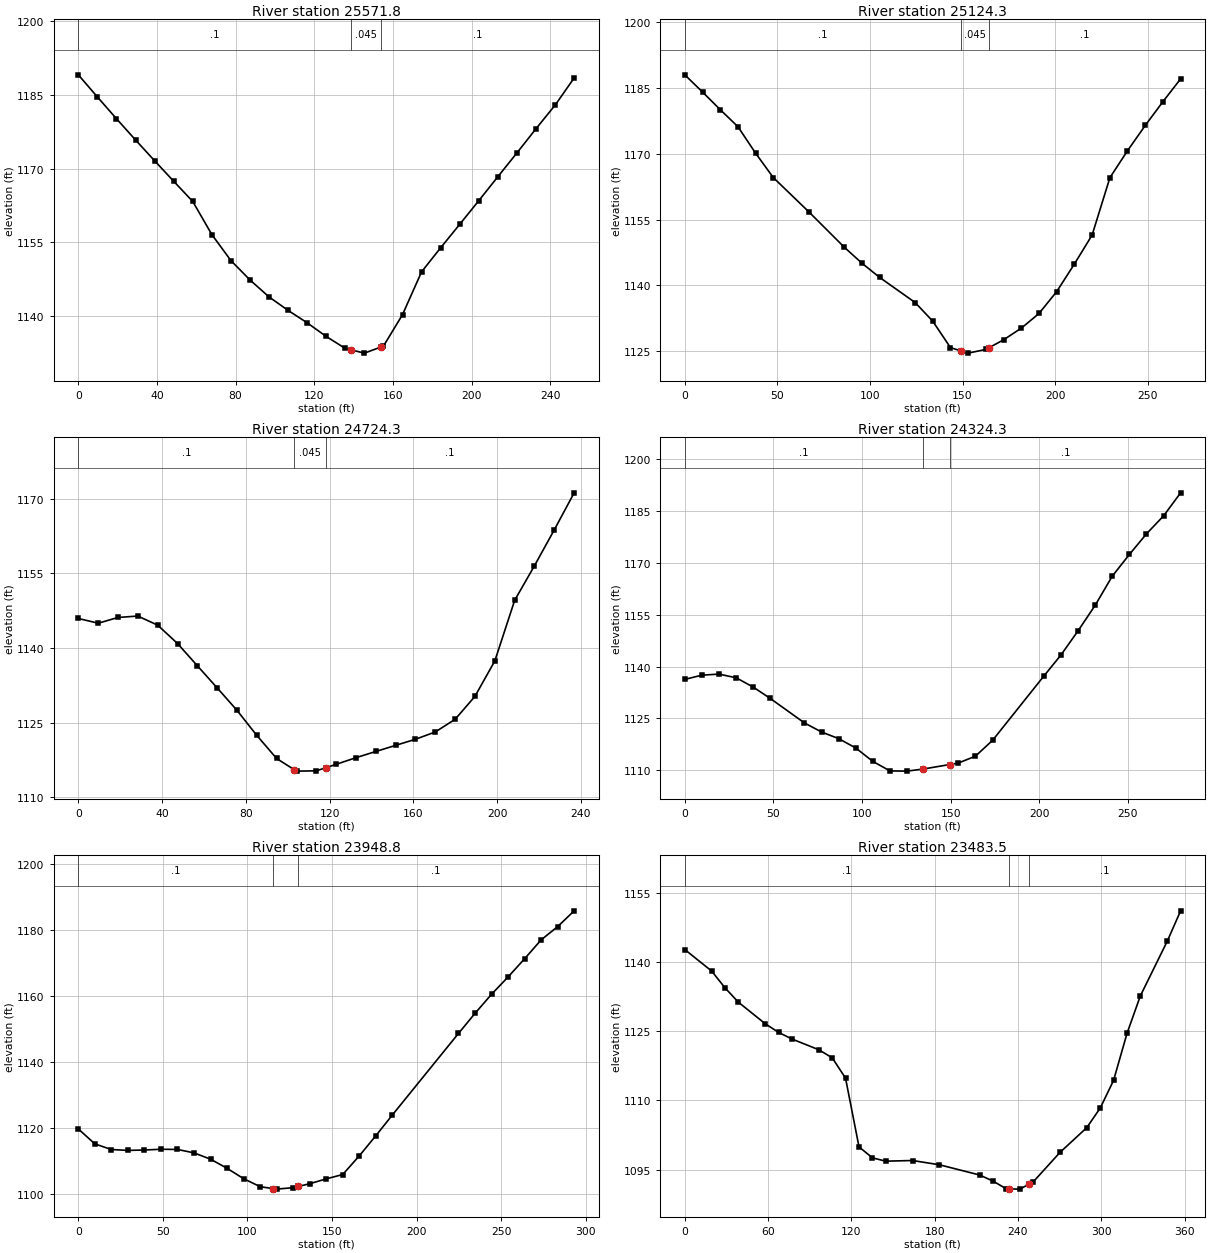
Type RM Length L Ch R = 1 ,25571.8 ,444.2,447.2,450.2
XS GIS Cut Line= 2
     1697914.589      261213.284     1698163.578      261172.836
#Sta/Elev= 29
       0 1189.12     9.7 1184.61    19.4 1180.17    29.1 1175.84    38.8  1171.6
    48.5 1167.43    58.2  1163.3    67.9 1156.57    77.6 1151.26    87.3 1147.31
      97 1143.85   106.7  1141.1   116.4 1138.57   126.1 1135.78   135.8 1133.34
   138.8 1133.05   145.5 1132.39   153.8 1133.61   155.2 1133.82   164.9 1140.24
   174.6 1148.97   184.3 1153.87     194 1158.65   203.7 1163.47   213.4 1168.36
   223.2 1173.26   232.8 1178.14   242.6 1182.98   252.2 1188.49
#Mann= 3 , 0 , 0
       0      .1       0   138.8    .045       0   153.8      .1       0
Bank Sta=138.8,153.8
XS Rating Curve= 0 ,0
Exp/Cntr=0.3,0.1

Type RM Length L Ch R = 1 ,25124.3 ,401.1,399.9,398.7
XS GIS Cut Line= 2
      1697991.52      261629.616     1698259.262      261622.471
#Sta/Elev= 28
       0    1188     9.6 1184.07    19.1 1180.08    28.7 1176.18    38.3 1170.11
    47.8 1164.59      67 1156.78    86.1 1148.74    95.7 1145.07   105.2 1141.85
   124.4 1136.12   133.9 1131.88   143.5 1125.84   149.2 1125.09     153 1124.59
   162.6 1125.43   164.2  1125.8   172.2 1127.63   181.8 1130.29   191.3 1133.62
   200.9 1138.63   210.4 1144.88     220  1151.5   229.6 1164.56   239.1  1170.7
   248.7 1176.47   258.3 1181.92   267.8 1187.08
#Mann= 3 , 0 , 0
       0      .1       0   149.2    .045       0   164.2      .1       0
Bank Sta=149.2,164.2
XS Rating Curve= 0 ,0
Exp/Cntr=0.3,0.1

Type RM Length L Ch R = 1 ,24724.3 ,388.8,400.6,412.3
XS GIS Cut Line= 2
     1698063.612      262032.198     1698299.646      262013.358
#Sta/Elev= 28
       0 1145.92     9.5 1144.97    18.9 1146.12    28.4 1146.41    37.9 1144.58
    47.4 1140.88    56.8 1136.44    66.3 1131.98    75.8 1127.46    85.2 1122.45
    94.7  1117.8   103.1 1115.55   104.2 1115.26   113.7 1115.32   118.1 1115.93
   123.1 1116.62   132.6 1117.96   142.1 1119.21   151.5 1120.43     161 1121.66
   170.5 1123.13     180 1125.69   189.4 1130.27   198.9 1137.38   208.4 1149.58
   217.8 1156.48   227.3 1163.72   236.8 1171.16
#Mann= 3 , 0 , 0
       0      .1       0   103.1    .045       0   118.1      .1       0
Bank Sta=103.1,118.1
XS Rating Curve= 0 ,0
Exp/Cntr=0.3,0.1

Type RM Length L Ch R = 1 ,24324.3 ,378,374.8,371.6
XS GIS Cut Line= 2
     1698006.916      262328.229     1698254.531      262458.539
#Sta/Elev= 27
       0 1136.28     9.6  1137.5    19.3 1137.81      29 1136.74    38.6 1134.05
    48.2 1130.77    67.5 1123.67    77.2 1121.03    86.8 1119.12    96.5  1116.4
   106.1 1112.52   115.8 1109.76   125.4  1109.7   134.6 1110.31   149.6 1111.62
   154.4 1112.05     164 1114.03   173.7 1118.63   202.6 1137.23   212.3 1143.37
   221.9 1150.33   231.6 1157.76   241.2 1166.17   250.9 1172.48   260.5 1178.43
   270.2 1183.67   279.8 1190.33
#Mann= 3 , 0 , 0
       0      .1       0   134.6    .045       0   149.6      .1       0
Bank Sta=134.6,149.6
XS Rating Curve= 0 ,0
Exp/Cntr=0.3,0.1

Type RM Length L Ch R = 1 ,23948.8 ,479.1,465.3,451.5
XS GIS Cut Line= 2
     1697795.201      262652.794     1698075.533      262738.453
#Sta/Elev= 30
       0 1119.63     9.8  1115.1    19.5  1113.4    29.3 1113.13    39.1 1113.25
    48.8 1113.48    58.6 1113.42    68.4 1112.38    78.2 1110.46    87.9 1107.71
    97.7 1104.56   107.5 1102.13     115 1101.56   117.2 1101.39     127 1101.83
     130  1102.2   136.8 1103.03   146.6 1104.51   156.3 1105.82   166.1 1111.49
   175.9 1117.61   185.6 1123.85   224.7 1148.59   234.5 1154.69   244.3 1160.49
     254  1165.7   263.8 1171.23   273.6 1176.97   283.4 1181.01   293.1 1185.77
#Mann= 3 , 0 , 0
       0      .1       0     115    .045       0     130      .1       0
Bank Sta=115,130
XS Rating Curve= 0 ,0
Exp/Cntr=0.3,0.1

Type RM Length L Ch R = 1 ,23483.5 ,463,466.8,470.6
XS GIS Cut Line= 2
      1697786.56       263186.91     1698126.202      263076.246
#Sta/Elev= 30
       0  1142.7    19.3 1138.05      29 1134.39    38.6 1131.29    57.9 1126.63
    67.6 1124.74    77.2 1123.31    96.5 1120.99   106.2 1119.24   115.8 1114.83
   125.5 1099.94   135.2 1097.55   144.8 1096.84   164.1 1096.98   183.4 1096.06
   212.4 1093.84     222 1092.53   231.7 1090.83   233.3 1090.82   241.4 1090.78
   248.3 1091.91     251 1092.35   270.3 1098.74   289.6 1104.11   299.3 1108.36
   308.9 1114.35   318.6 1124.55   328.2 1132.67   347.6 1144.53   357.2 1151.09
#Mann= 3 , 0 , 0
       0      .1       0   233.3    .045       0   248.3      .1       0
Bank Sta=233.3,248.3
XS Rating Curve= 0 ,0
Exp/Cntr=0.3,0.1

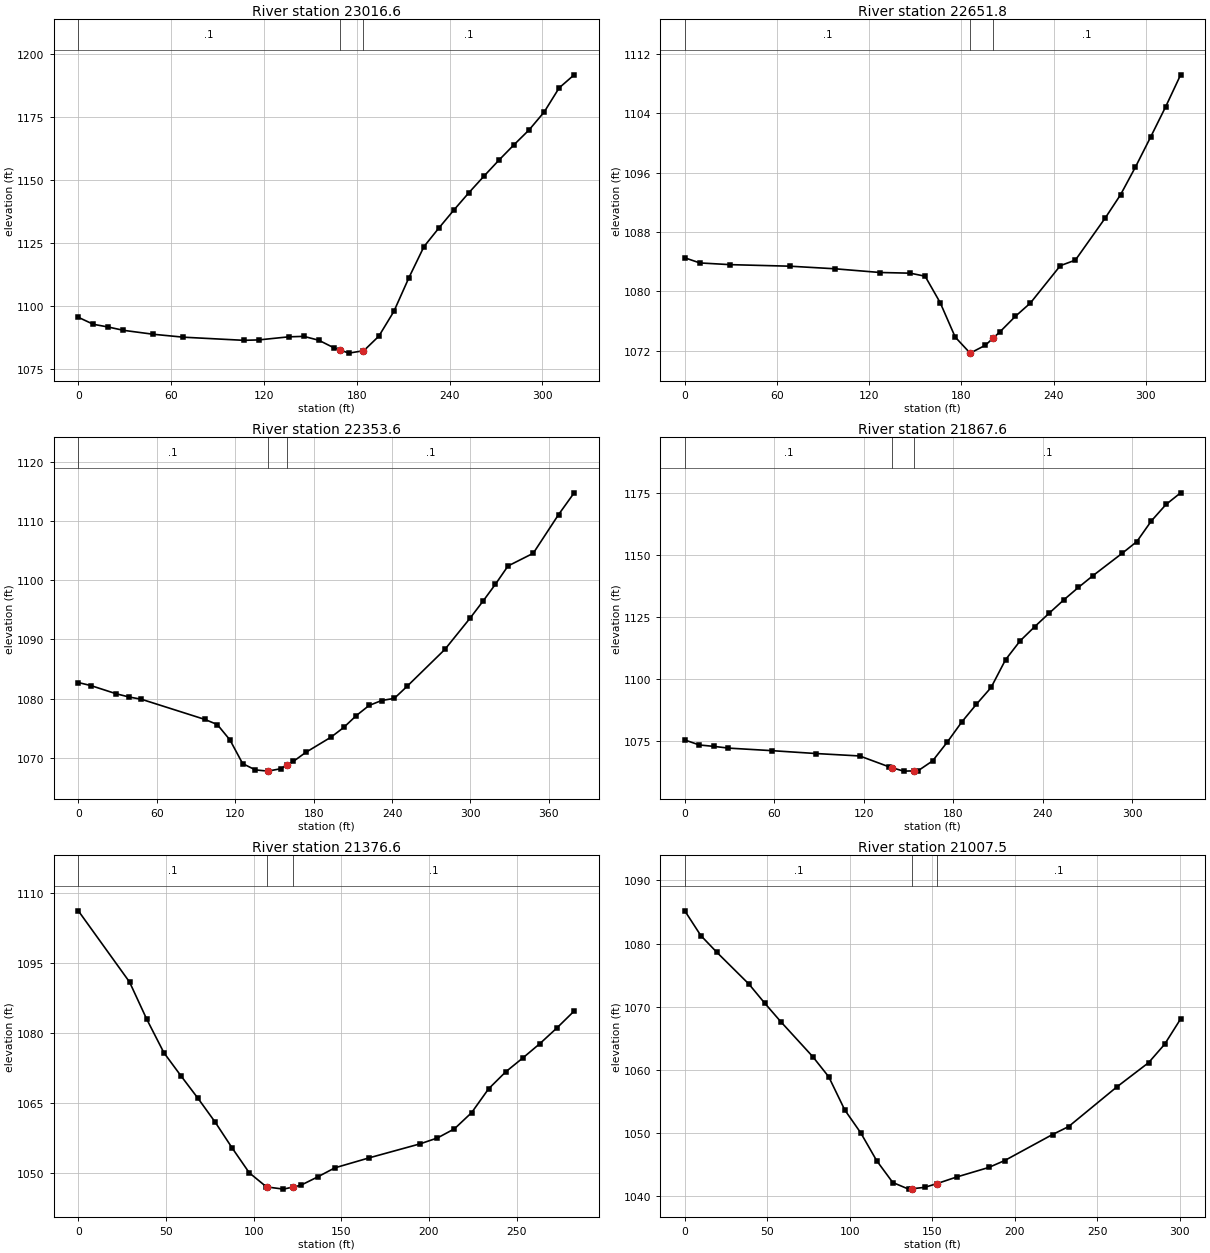
Type RM Length L Ch R = 1 ,23016.6 ,378.7,364.8,350.9
XS GIS Cut Line= 2
     1697836.974      263601.003     1698154.103      263553.582
#Sta/Elev= 30
       0 1095.58     9.7 1092.81    19.4 1091.72    29.2 1090.42    48.6 1088.85
      68  1087.7   106.9 1086.46   116.6 1086.62     136 1087.84   145.8 1088.03
   155.5 1086.49   165.2 1083.51   169.1 1082.66   174.9 1081.39   184.1 1082.31
   184.6 1082.36   194.3  1088.1     204 1097.88   213.8 1111.33   223.5 1123.59
   233.2 1130.99   242.9 1138.12   252.6 1144.97   262.4 1151.56   272.1 1157.91
   281.8 1163.97   291.5 1169.82   301.2 1176.87   310.9 1186.44   320.6 1191.61
#Mann= 3 , 0 , 0
       0      .1       0   169.1    .045       0   184.1      .1       0
Bank Sta=169.1,184.1
XS Rating Curve= 0 ,0
Exp/Cntr=0.3,0.1

Type RM Length L Ch R = 1 ,22651.8 ,300.2,298.1,296.1
XS GIS Cut Line= 2
     1698095.378      263976.106     1698328.322      263752.824
#Sta/Elev= 24
       0  1084.5     9.8 1083.81    29.3 1083.58    68.4 1083.37    97.8 1083.02
   127.1 1082.52   146.7 1082.43   156.4 1082.02   166.2 1078.46     176 1073.81
   185.7 1071.65   195.6 1072.71   200.7 1073.68   205.3 1074.56   215.1  1076.6
   224.9  1078.4   244.4 1083.44   254.2 1084.19   273.8 1089.92   283.6    1093
   293.3 1096.74   303.1 1100.75   312.9 1104.84   322.7 1109.17
#Mann= 3 , 0 , 0
       0      .1       0   185.7    .045       0   200.7      .1       0
Bank Sta=185.7,200.7
XS Rating Curve= 0 ,0
Exp/Cntr=0.3,0.1

Type RM Length L Ch R = 1 ,22353.6 ,468.2,485.9,503.7
XS GIS Cut Line= 3
     1698402.542      264090.337       1698647.2      263803.453
      1698648.64      263801.764
#Sta/Elev= 30
       0 1082.72     9.7  1082.2      29 1080.82    38.7 1080.28    48.3 1079.89
    96.7 1076.49   106.3 1075.62     116 1073.01   125.7 1069.01   135.4 1067.95
     145 1067.74   154.7 1068.14     160 1068.81   164.4 1069.37     174 1070.91
   193.4  1073.5     203 1075.12   212.7 1077.14   222.4 1078.84     232 1079.68
   241.7 1080.04   251.4 1082.06   280.4 1088.32   299.7 1093.61   309.4 1096.43
     319 1099.32   328.7 1102.43     348 1104.58   367.4 1111.13   379.3  1114.8
#Mann= 3 , 0 , 0
       0      .1       0     145    .045       0     160      .1       0
Bank Sta=145,160
XS Rating Curve= 0 ,0
Exp/Cntr=0.3,0.1

Type RM Length L Ch R = 1 ,21867.6 ,491.7,490.9,490
XS GIS Cut Line= 2
     1698495.988      264406.417     1698827.888      264387.032
#Sta/Elev= 29
       0 1075.43     9.8 1073.41    19.6 1072.84    29.3 1072.15    58.7 1071.11
      88 1069.96   117.3 1068.98   136.9 1064.61     139 1064.24   146.7 1062.86
     154 1062.97   156.4    1063   166.2    1067     176 1074.56   185.8 1082.74
   195.6 1089.88   205.4 1096.62   215.1 1107.83   224.9 1115.45   234.7 1121.19
   244.5 1126.69   254.2    1132     264 1137.03   273.8 1141.79   293.4 1150.83
   303.1 1155.48   312.9 1163.86   322.7 1170.48   332.5 1175.18
#Mann= 3 , 0 , 0
       0      .1       0     139    .045       0     154      .1       0
Bank Sta=139,154
XS Rating Curve= 0 ,0
Exp/Cntr=0.3,0.1

Type RM Length L Ch R = 1 ,21376.6 ,374.7,369,363.3
XS GIS Cut Line= 2
     1698335.483      264839.595     1698616.763      264810.347
#Sta/Elev= 27
       0 1106.12    29.2  1090.9      39 1082.96    48.8 1075.78    58.5 1070.85
    68.3    1066      78 1060.96    87.8 1055.37    97.5  1050.1   107.3 1047.09
   107.7 1047.07     117 1046.61   122.7 1047.08   126.8 1047.42   136.5 1049.22
   146.3 1051.16   165.8 1053.29     195  1056.3   204.8 1057.55   214.5  1059.5
   224.3 1062.96     234 1068.06   243.8  1071.7   253.5 1074.65   263.3 1077.74
     273 1081.09   282.8 1084.69
#Mann= 3 , 0 , 0
       0      .1       0   107.7    .045       0   122.7      .1       0
Bank Sta=107.7,122.7
XS Rating Curve= 0 ,0
Exp/Cntr=0.3,0.1

Type RM Length L Ch R = 1 ,21007.5 ,281.9,283.3,284.6
XS GIS Cut Line= 2
     1698514.642      265180.218     1698796.099      265075.365
#Sta/Elev= 25
       0 1085.19     9.7 1081.27    19.4 1078.62    38.8 1073.59    48.4 1070.56
    58.1 1067.63    77.5 1062.08    87.2 1058.88    96.9 1053.63   106.6 1049.99
   116.3 1045.56     126 1042.12   135.6 1041.07   137.6 1041.13   145.3 1041.35
   152.6 1041.93   164.7 1042.99   184.1  1044.5   193.8  1045.6   222.8 1049.73
   232.5 1050.98   261.6 1057.24     281 1061.12   290.7 1064.03   300.4 1068.05
#Mann= 3 , 0 , 0
       0      .1       0   137.6    .045       0   152.6      .1       0
Bank Sta=137.6,152.6
XS Rating Curve= 0 ,0
Exp/Cntr=0.3,0.1

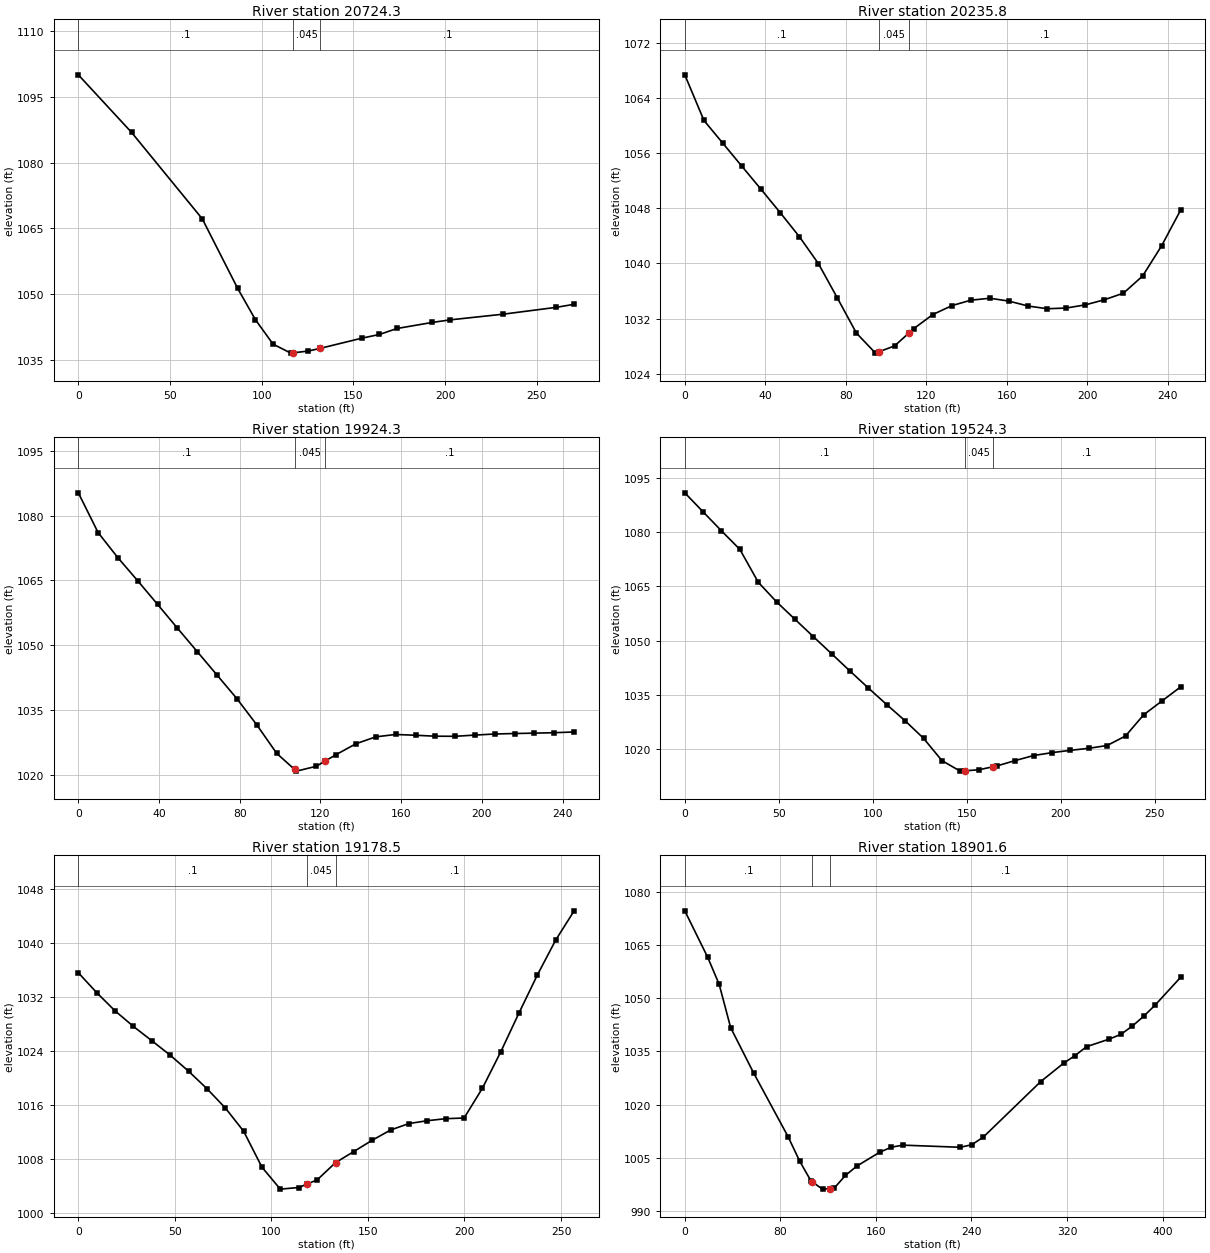
Type RM Length L Ch R = 1 ,20724.3 ,479.9,488.6,497.3
XS GIS Cut Line= 2
     1698654.967      265420.844     1698913.492      265341.666
#Sta/Elev= 18
       0 1100.05      29 1086.93    67.6 1067.19    86.9 1051.32    96.6 1044.17
   106.2 1038.61   115.9 1036.56     117 1036.62   125.5 1037.04     132 1037.66
   154.5 1039.96   164.2 1040.82   173.8 1042.18   193.1 1043.57   202.8 1044.15
   231.8 1045.45   260.7 1047.01   270.4  1047.7
#Mann= 3 , 0 , 0
       0      .1       0     117    .045       0     132      .1       0
Bank Sta=117,132
XS Rating Curve= 0 ,0
Exp/Cntr=0.3,0.1

Type RM Length L Ch R = 1 ,20235.8 ,321.4,311.2,301
XS GIS Cut Line= 2
     1698675.462      265846.894      1698920.97      265869.336
#Sta/Elev= 29
       0 1067.32     9.5 1060.72      19 1057.38    28.4 1054.07    37.9 1050.74
    47.4 1047.37    56.9  1043.9    66.4 1039.99    75.9 1034.97    85.3 1029.92
    94.8 1027.01    96.4 1027.19   104.3 1028.06   111.4 1029.92   113.8 1030.55
   123.3  1032.6   132.8 1033.89   142.2 1034.68   151.7 1034.96   161.2 1034.54
   170.7 1033.83   180.2 1033.44   189.6 1033.54   199.1    1034   208.6 1034.74
   218.1  1035.7   227.6 1038.18     237 1042.53   246.5 1047.73
#Mann= 3 , 0 , 0
       0      .1       0    96.4    .045       0   111.4      .1       0
Bank Sta=96.4,111.4
XS Rating Curve= 0 ,0
Exp/Cntr=0.3,0.1

Type RM Length L Ch R = 1 ,19924.3 ,386.6,400,413.3
XS GIS Cut Line= 2
     1698712.648      266196.743     1698942.113       266108.95
#Sta/Elev= 28
       0 1085.25     9.8 1076.05    19.6 1070.24    29.5 1064.86    39.3 1059.42
    49.1 1053.94      59 1048.47    68.8 1043.05    78.6 1037.61    88.4 1031.59
    98.3 1024.97   107.2 1021.24   108.1 1020.86   117.9 1021.98   122.2 1023.16
   127.8  1024.7   137.6  1027.2   147.4 1028.79   157.2 1029.34   167.1 1029.16
   176.9 1028.94   186.7 1028.92   196.6  1029.2   206.4 1029.45   216.2 1029.56
     226 1029.65   235.9 1029.75   245.7 1029.92
#Mann= 3 , 0 , 0
       0      .1       0   107.2    .045       0   122.2      .1       0
Bank Sta=107.2,122.2
XS Rating Curve= 0 ,0
Exp/Cntr=0.3,0.1

Type RM Length L Ch R = 1 ,19524.3 ,339.7,345.7,351.7
XS GIS Cut Line= 2
     1698713.359      266504.053     1698970.372      266563.404
#Sta/Elev= 30
       0 1090.92     9.8 1085.62    19.5  1080.4    29.3 1075.26    39.1 1066.15
    48.8 1060.75    58.6 1055.91    68.4  1051.1    78.2 1046.32    87.9 1041.57
    97.7 1036.86   107.5 1032.26   117.2 1027.81     127 1022.97   136.8 1016.79
   146.5 1013.87     149 1013.96   156.3 1014.23     164 1015.08   166.1 1015.31
   175.8  1016.8   185.6 1018.19   195.4 1018.99   205.2 1019.63   214.9 1020.19
   224.7 1020.96   234.5 1023.61   244.2  1029.5     254 1033.34   263.8 1037.19
#Mann= 3 , 0 , 0
       0      .1       0     149    .045       0     164      .1       0
Bank Sta=149,164
XS Rating Curve= 0 ,0
Exp/Cntr=0.3,0.1

Type RM Length L Ch R = 1 ,19178.5 ,284.9,276.8,268.8
XS GIS Cut Line= 2
     1698604.989      266790.152     1698831.343       266911.53
#Sta/Elev= 29
       0 1035.54     9.5  1032.6      19  1029.9    28.5  1027.6      38 1025.49
    47.6 1023.33    57.1 1020.96    66.6 1018.38    76.1 1015.53    85.6 1012.08
    95.1 1006.75   104.6  1003.5   114.2 1003.74   118.2 1004.22   123.7 1004.87
   133.2 1007.42   142.7 1009.07   152.2 1010.74   161.7 1012.25   171.2 1013.21
   180.7 1013.63   190.2 1013.93   199.8 1014.03   209.3 1018.45   218.8 1023.84
   228.3 1029.63   237.8 1035.24   247.3 1040.41   256.8 1044.71
#Mann= 3 , 0 , 0
       0      .1       0   118.2    .045       0   133.2      .1       0
Bank Sta=118.2,133.2
XS Rating Curve= 0 ,0
Exp/Cntr=0.3,0.1

Type RM Length L Ch R = 1 ,18901.6 ,550.8,572.3,593.8
XS GIS Cut Line= 3
     1698489.262      267084.997     1698888.992      267140.383
     1698900.418      267141.966
#Sta/Elev= 30
       0 1074.57    19.2 1061.47    28.8 1053.85    38.4 1041.68    57.6 1028.95
    86.5 1010.98    96.1 1004.16   105.7   998.5   106.6  998.29   115.3  996.24
   121.6  996.38   124.9  996.45   134.5  1000.1   144.1 1002.74   163.3 1006.65
     173 1008.05   182.6 1008.62   230.6 1008.02   240.2 1008.72   249.8 1010.85
   297.9 1026.49   317.1 1031.67   326.7 1033.83   336.3 1036.32   355.5 1038.49
   365.1 1039.81   374.7 1042.14   384.3 1044.93   393.9 1048.09   415.1 1055.86
#Mann= 3 , 0 , 0
       0      .1       0   106.6    .045       0   121.6      .1       0
Bank Sta=106.6,121.6
XS Rating Curve= 0 ,0
Exp/Cntr=0.3,0.1