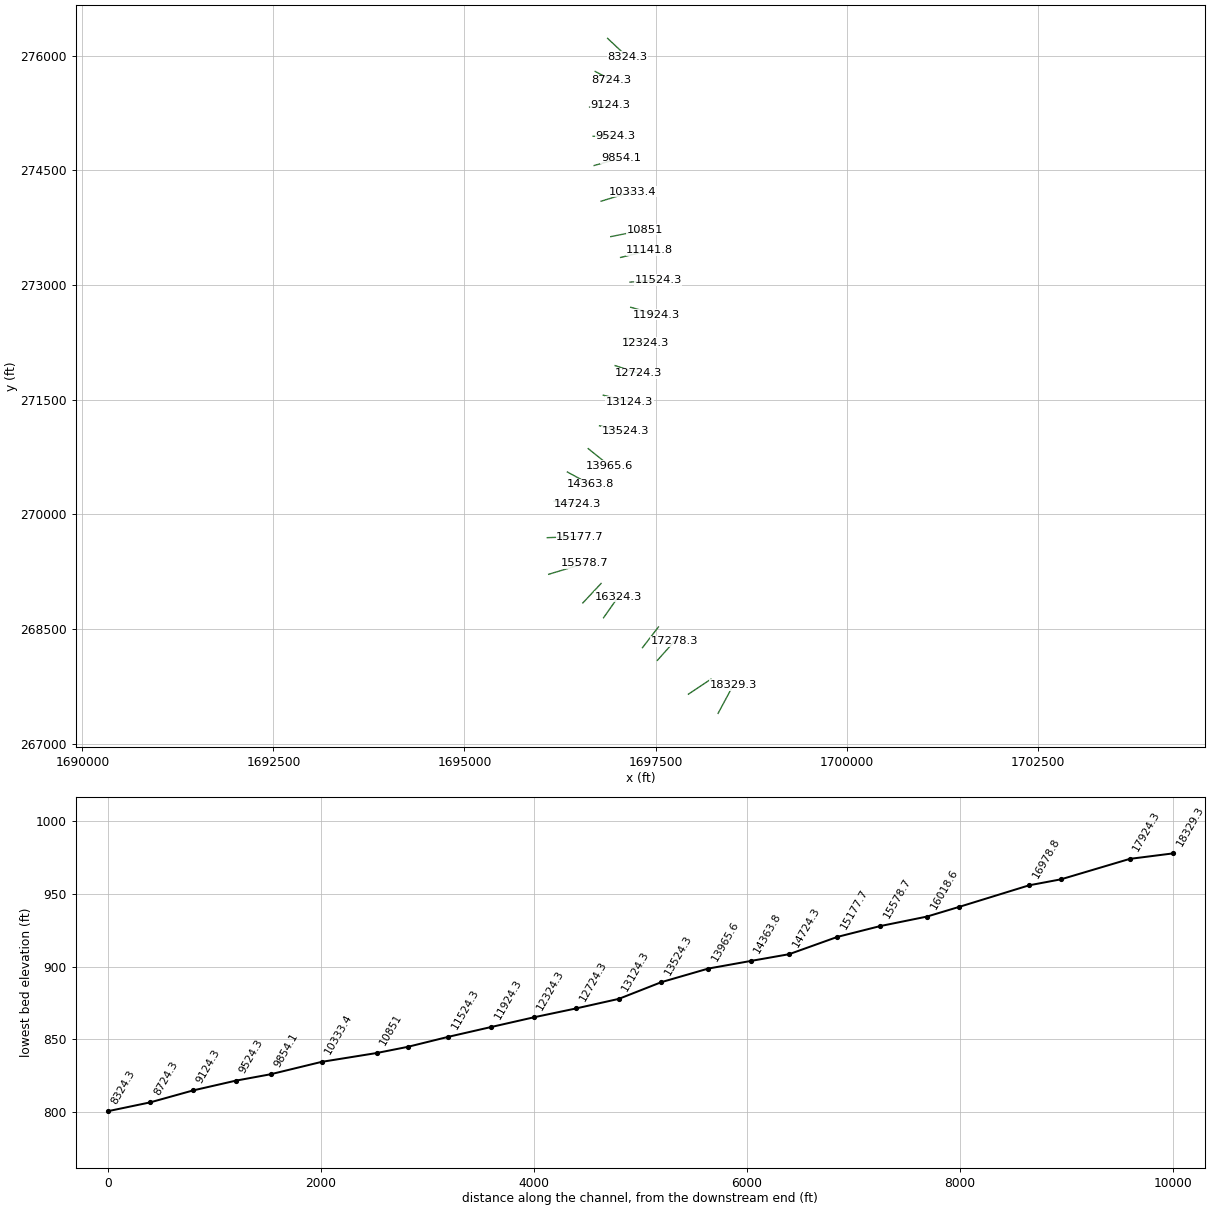
HEC-RAS study RICHCRK.prj: RICHCRK

--- RICHCRK.g01 (geometry) --- (continued)

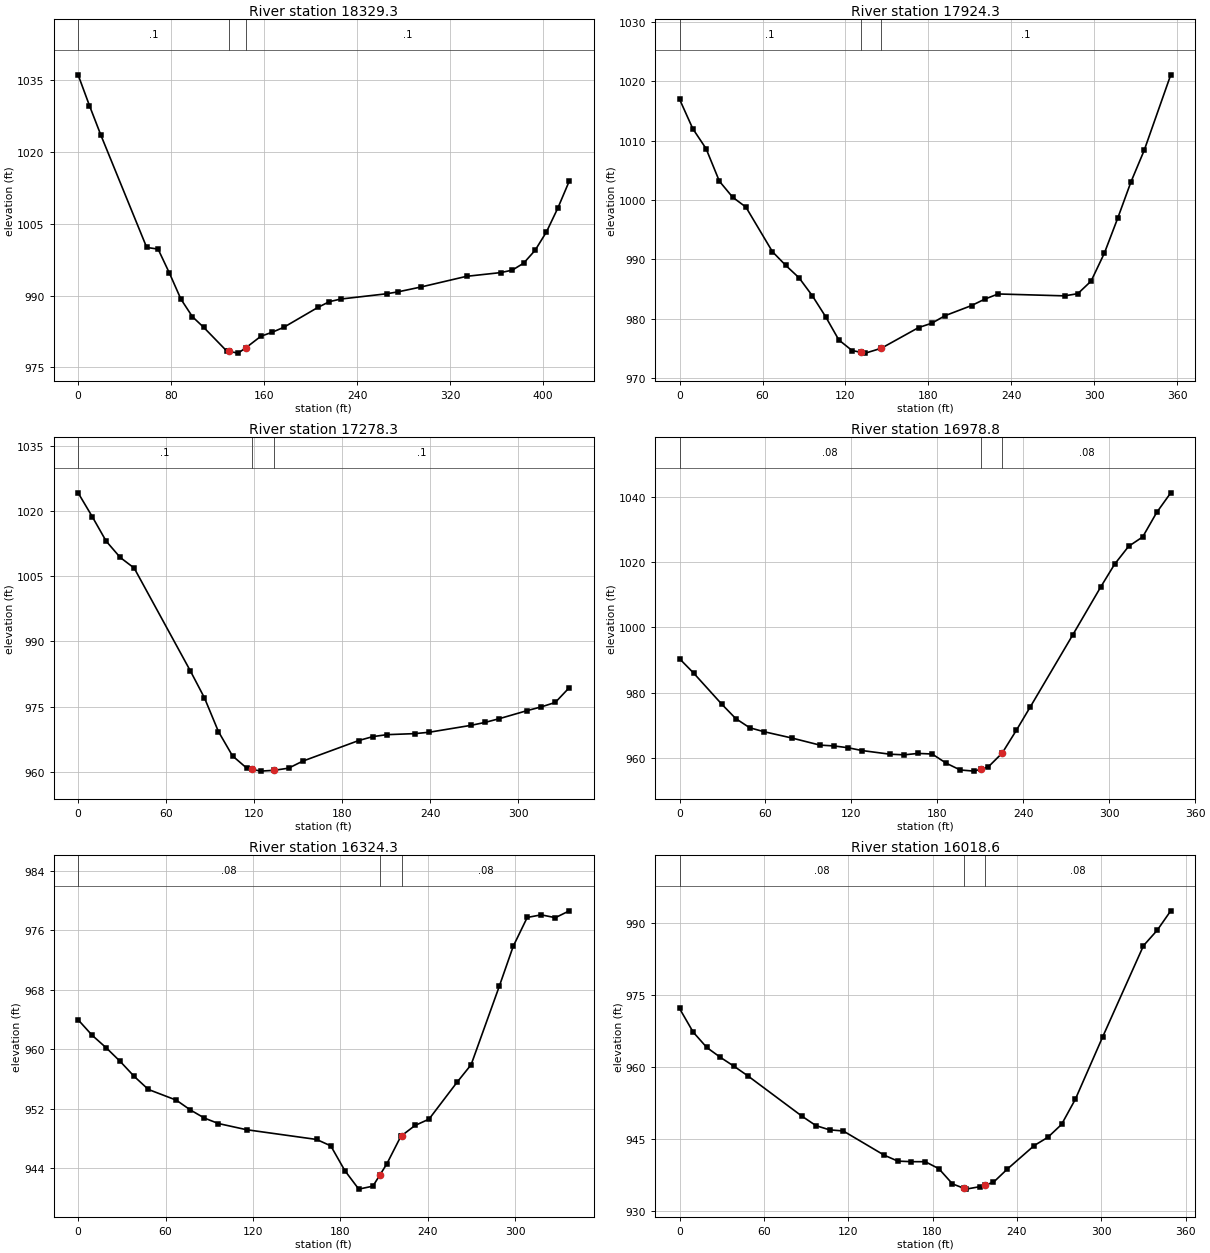
Type RM Length L Ch R = 1 ,18329.3 ,415.9,404.9,394
XS GIS Cut Line= 2
     1698318.373      267397.976     1698518.578      267770.028
#Sta/Elev= 30
       0 1036.17     9.8 1029.71    19.6 1023.55      59 1000.08    68.8  999.73
    78.6  994.68    88.4  989.28    98.3   985.6   108.1  983.35   127.7  978.45
   129.5  978.36   137.6  977.98   144.5  979.13   157.2  981.51     167  982.35
   176.9  983.38   206.3  987.55   216.2  988.75     226  989.29   265.3  990.39
   275.1  990.79   294.8   991.8   334.1  994.04   363.5  994.82   373.4  995.33
   383.2  996.79     393  999.46   402.8 1003.31   412.7 1008.36   422.5 1013.99
#Mann= 3 , 0 , 0
       0      .1       0   129.5    .045       0   144.5      .1       0
Bank Sta=129.5,144.5
XS Rating Curve= 0 ,0
Exp/Cntr=0.3,0.1

Type RM Length L Ch R = 1 ,17924.3 ,640.4,646,651.7
XS GIS Cut Line= 2
     1697930.613      267649.135     1698226.203      267846.195
#Sta/Elev= 30
       0 1017.01     9.6 1012.03    19.2 1008.67    28.8 1003.19    38.4 1000.49
      48  998.82    67.2   991.3    76.8     989    86.4  986.91      96  983.89
   105.6  980.37   115.2  976.43   124.8  974.64   130.9  974.37   134.4  974.21
   145.9  975.03   172.8  978.51   182.4  979.25     192  980.52   211.2  982.23
   220.8  983.32   230.4  984.18   278.4  983.86     288  984.23   297.6  986.35
   307.2  991.06   316.8  996.92   326.4 1003.05     336 1008.39   355.2 1021.11
#Mann= 3 , 0 , 0
       0      .1       0   130.9    .045       0   145.9      .1       0
Bank Sta=130.9,145.9
XS Rating Curve= 0 ,0
Exp/Cntr=0.3,0.1

Type RM Length L Ch R = 1 ,17278.3 ,297.3,299.1,300.8
XS GIS Cut Line= 2
     1697524.473      268091.685     1697747.613      268341.138
#Sta/Elev= 27
       0 1024.17     9.6 1018.71    19.1 1013.06    28.7  1009.3    38.2 1006.86
    76.5  983.19    86.1  976.99    95.6  969.25   105.2  963.65   114.8  960.86
   118.6  960.57   124.3  960.14   133.6  960.33   143.4  960.82     153  962.43
   191.2  967.18   200.8  968.08   210.4  968.53   229.5  968.77   239.1  969.08
   267.8  970.68   277.3  971.35   286.9   972.2     306  974.07   315.6  974.92
   325.1  975.94   334.7  979.36
#Mann= 3 , 0 , 0
       0      .1       0   118.6    .045       0   133.6      .1       0
Bank Sta=118.6,133.6
XS Rating Curve= 0 ,0
Exp/Cntr=0.3,0.1

Type RM Length L Ch R = 1 ,16978.8 ,653.4,654.4,655.4
XS GIS Cut Line= 2
     1697328.559      268256.665      1697538.17       268528.14
#Sta/Elev= 30
       0  990.44     9.8  986.06    29.4  976.56    39.2  972.13      49   969.3
    58.8  968.11    78.4  966.16      98  963.99   107.8  963.73   117.6  963.19
   127.4  962.32     147   961.2   156.8  961.01   166.6  961.44   176.4  961.26
   186.2  958.45     196  956.37   205.8  956.02   210.3  956.62   215.6  957.32
   225.3  961.54   235.2  968.53     245  975.74   274.4   997.6     294 1012.32
   303.8 1019.37   313.6 1024.85   323.4 1027.72   333.2 1035.22     343 1041.22
#Mann= 3 , 0 , 0
       0     .08       0   210.3    .045       0   225.3     .08       0
Bank Sta=210.3,225.3
XS Rating Curve= 0 ,0
Exp/Cntr=0.3,0.1

Type RM Length L Ch R = 1 ,16324.3 ,308.8,305.6,302.4
XS GIS Cut Line= 2
     1696819.685      268648.813     1697014.039      268924.258
#Sta/Elev= 30
       0  963.97     9.6  961.89    19.3   960.2    28.9  958.37    38.5  956.36
    48.2  954.61    67.4  953.17      77  951.86    86.7  950.76    96.3  950.03
   115.6   949.2   163.7  947.89   173.4  947.03     183  943.72   192.6  941.22
   202.3  941.62   207.1  943.12   211.9  944.63   221.5  948.32   222.1  948.41
   231.2  949.77   240.8  950.62   260.1  955.59   269.7  957.93     289  968.45
   298.6  973.84   308.2  977.71   317.8  978.06   327.5  977.68   337.1   978.6
#Mann= 3 , 0 , 0
       0     .08       0   207.1    .045       0   222.1     .08       0
Bank Sta=207.1,222.1
XS Rating Curve= 0 ,0
Exp/Cntr=0.3,0.1

Type RM Length L Ch R = 1 ,16018.6 ,451.7,439.9,428.1
XS GIS Cut Line= 2
      1696548.55      268842.069     1696787.473      269097.164
#Sta/Elev= 30
       0  972.13     9.7  967.21    19.4     964    29.1  961.94    38.8  960.08
    48.5  958.11    87.4  949.62    97.1  947.71   106.8  946.83   116.5   946.6
   145.6  941.56   155.3  940.32     165   940.2   174.8   940.2   184.5  938.74
   194.2  935.57   202.5  934.64   203.9  934.48   213.6  934.99   217.5  935.35
   223.3  935.89     233   938.6   252.4  943.57   262.1  945.29   271.8  947.96
   281.6   953.2     301  966.17   330.1  985.22   339.8  988.41   349.5  992.48
#Mann= 3 , 0 , 0
       0     .08       0   202.5    .045       0   217.5     .08       0
Bank Sta=202.5,217.5
XS Rating Curve= 0 ,0
Exp/Cntr=0.3,0.1

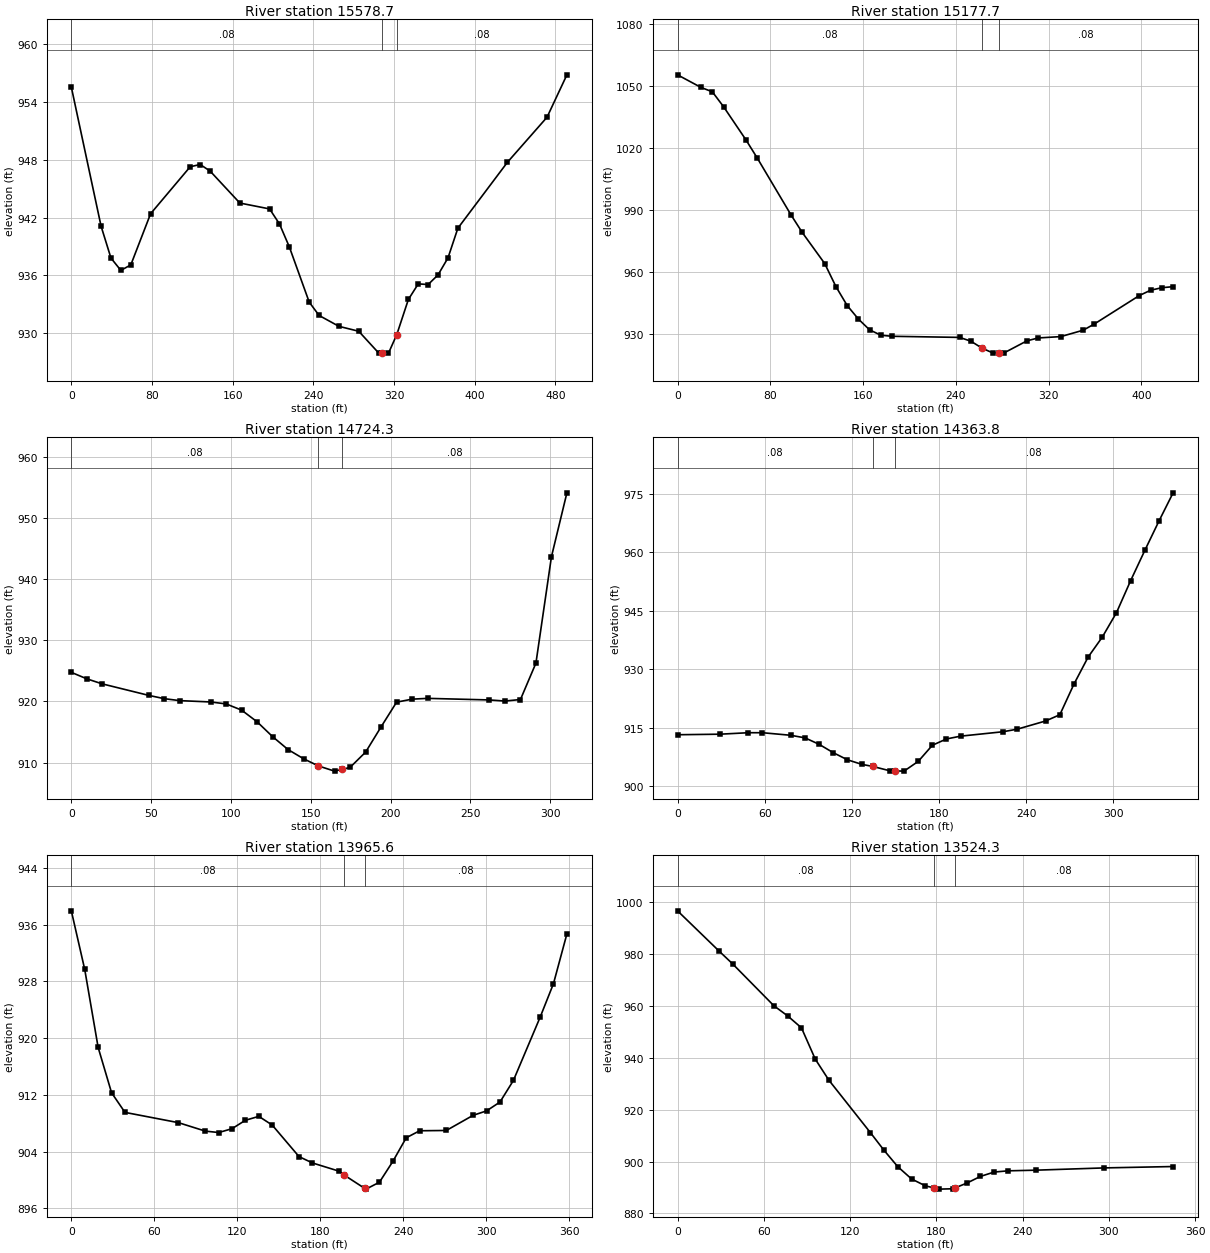
Type RM Length L Ch R = 1 ,15578.7 ,406.7,400.7,394.8
XS GIS Cut Line= 2
     1696102.148      269217.283     1696572.607      269359.172
#Sta/Elev= 30
       0  955.55    29.5  941.11    39.3   937.8    49.1  936.52      59  937.09
    78.6   942.4   117.9  947.28   127.8  947.51   137.6  946.83   167.1  943.51
   196.6   942.9   206.4  941.34   216.2  938.95   235.9  933.22   245.7  931.84
   265.4  930.71     285   930.2   304.7  927.95   307.7  927.94   314.5  927.93
   322.7  929.85   334.2   933.5     344  935.12   353.8  935.05   363.6  936.05
   373.5  937.82   383.3   940.9   432.4  947.74   471.7  952.42   491.4  956.82
#Mann= 3 , 0 , 0
       0     .08       0   307.7    .045       0   322.7     .08       0
Bank Sta=307.7,322.7
XS Rating Curve= 0 ,0
Exp/Cntr=0.3,0.1

Type RM Length L Ch R = 1 ,15177.7 ,456.4,453.4,450.4
XS GIS Cut Line= 3
     1696082.978      269696.013     1696093.564      269696.372
     1696510.021      269710.464
#Sta/Elev= 30
       0 1055.36    20.3 1049.24      30 1047.14    39.7 1039.92      59 1023.84
    68.7 1015.08    97.8  987.53   107.5     979   126.9  963.92   136.6  952.72
   146.3  943.55     156  936.98   165.6  931.79   175.3  929.18     185  928.66
   243.2  928.12   252.9   926.3   262.6   922.9   272.2   920.5   277.6  920.62
   281.9  920.72   301.3  926.46     311  927.86   330.4   928.5   349.8  931.61
   359.4  934.62   398.2  948.41   407.9  950.98   417.6   952.2   427.3   952.7
#Mann= 3 , 0 , 0
       0     .08       0   262.6    .045       0   277.6     .08       0
Bank Sta=262.6,277.6
XS Rating Curve= 0 ,0
Exp/Cntr=0.3,0.1

Type RM Length L Ch R = 1 ,14724.3 ,369.4,360.5,351.5
XS GIS Cut Line= 2
     1696169.667      270173.739     1696478.602      270142.779
#Sta/Elev= 28
       0  924.77     9.7  923.71    19.4  922.88    48.5     921    58.2  920.46
    67.9  920.14    87.3  919.92      97   919.6   106.7  918.58   116.4  916.67
   126.1  914.24   135.8  912.12   145.5  910.62   154.7  909.45   164.9  908.59
   169.7  908.89   174.6  909.19   184.4  911.71     194  915.81   203.8  919.89
   213.5  920.38   223.2  920.51     262  920.25   271.7  920.07   281.4  920.32
   291.1  926.29   300.8  943.69   310.5  954.18
#Mann= 3 , 0 , 0
       0     .08       0   154.7    .045       0   169.7     .08       0
Bank Sta=154.7,169.7
XS Rating Curve= 0 ,0
Exp/Cntr=0.3,0.1

Type RM Length L Ch R = 1 ,14363.8 ,402.3,398.2,394.1
XS GIS Cut Line= 2
       1696346.3       270554.84     1696646.309      270392.203
#Sta/Elev= 30
       0  913.26    29.2   913.4    48.8  913.78    58.5  913.78      78  913.12
    87.8  912.46    97.5  910.81   107.2  908.67     117  906.84   126.8  905.68
   134.6  905.12   146.2  904.02   149.6  903.99     156  903.93   165.8  906.44
   175.5  910.56   185.2  912.18     195   912.9   224.2  914.03     234  914.69
   253.5  916.79   263.3  918.39     273  926.23   282.8  933.19   292.5  938.28
   302.3  944.56     312  952.73   321.8  960.51   331.5  968.01   341.3  975.29
#Mann= 3 , 0 , 0
       0     .08       0   134.6    .045       0   149.6     .08       0
Bank Sta=134.6,149.6
XS Rating Curve= 0 ,0
Exp/Cntr=0.3,0.1

Type RM Length L Ch R = 1 ,13965.6 ,430.8,441.2,451.6
XS GIS Cut Line= 2
     1696619.562      270860.391      1696899.01      270635.933
#Sta/Elev= 30
       0  937.94     9.7  929.67    19.4  918.68    29.1  912.29    38.8  909.52
    77.5  908.07    96.9  906.88   106.6  906.68   116.2  907.22   125.9  908.41
   135.6  908.96   145.3  907.73   164.7  903.28   174.4  902.39   193.8  901.22
   197.2   900.7   212.2   898.8   213.1   898.7   222.8  899.67   232.5   902.6
   242.2  905.94   251.9  906.93   271.2  906.97   290.6  909.11   300.3  909.73
     310  910.98   319.7  914.02   339.1  922.97   348.7  927.68   358.4  934.69
#Mann= 3 , 0 , 0
       0     .08       0   197.2    .045       0   212.2     .08       0
Bank Sta=197.2,212.2
XS Rating Curve= 0 ,0
Exp/Cntr=0.3,0.1

Type RM Length L Ch R = 1 ,13524.3 ,400.5,399.9,399.4
XS GIS Cut Line= 2
     1696767.252      271159.047     1697103.915      271084.867
#Sta/Elev= 24
       0  996.74    28.7  981.32    38.3  976.28      67  960.12    76.6  956.19
    86.2  951.59    95.8  939.51   105.3  931.37   134.1  911.18   143.6  904.35
   153.2     898   162.8  893.26   172.4   890.6   178.3  889.83     182  889.34
   191.5  889.48   193.3  889.88   201.1  891.63   210.7  894.25   220.2  895.92
   229.8   896.4     249  896.65   296.9  897.53   344.7  898.06
#Mann= 3 , 0 , 0
       0     .08       0   178.3    .045       0   193.3     .08       0
Bank Sta=178.3,193.3
XS Rating Curve= 0 ,0
Exp/Cntr=0.3,0.1

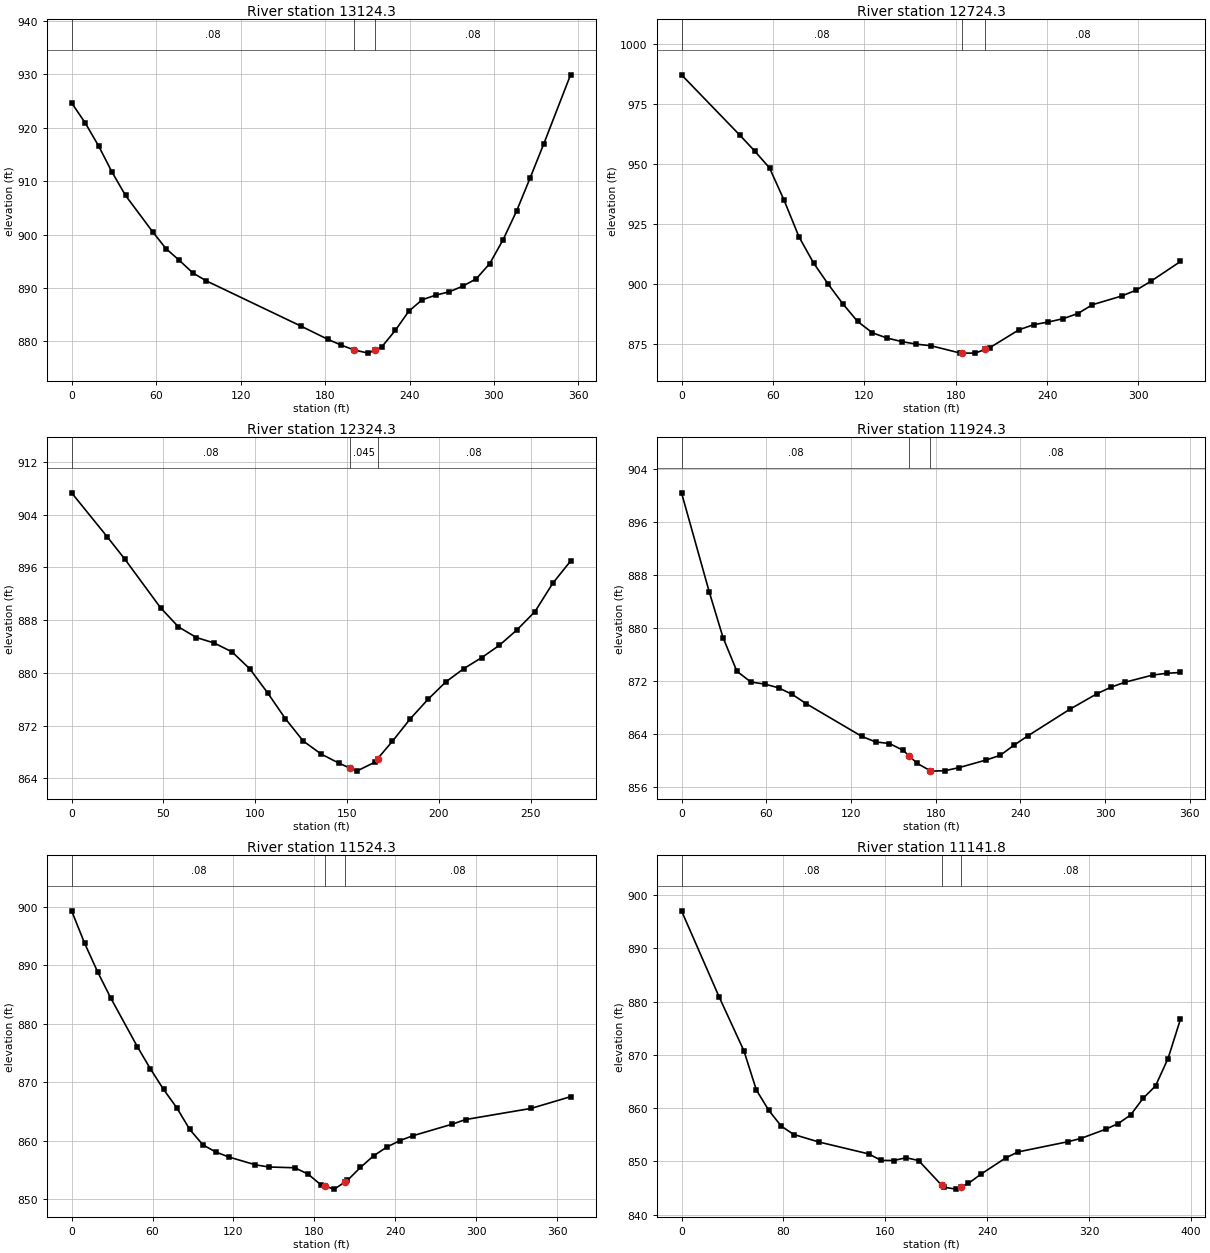
Type RM Length L Ch R = 1 ,13124.3 ,401.7,400,398.2
XS GIS Cut Line= 2
     1696816.329      271559.152     1697160.891      271476.128
#Sta/Elev= 30
       0  924.66     9.6  920.93    19.2  916.59    28.7   911.7    38.3  907.33
    57.5  900.55      67  897.39    76.6  895.16    86.2  892.81    95.8  891.33
   162.8  882.89     182   880.4   191.6  879.31   200.7  878.41   210.7  877.82
   215.7  878.43   220.3  878.99   229.9  882.07   239.5  885.67     249  887.81
   258.6  888.67   268.2  889.29   277.8  890.35   287.4  891.73     297  894.58
   306.5  899.06   316.1  904.44   325.7  910.63   335.3  916.94   354.4  929.91
#Mann= 3 , 0 , 0
       0     .08       0   200.7    .045       0   215.7     .08       0
Bank Sta=200.7,215.7
XS Rating Curve= 0 ,0
Exp/Cntr=0.3,0.1

Type RM Length L Ch R = 1 ,12724.3 ,398.4,399.9,401.5
XS GIS Cut Line= 2
     1696971.128       271946.15     1697282.682      271844.894
#Sta/Elev= 30
       0  987.06    38.5  961.82    48.2  955.24    57.8   948.3    67.4  934.81
    77.1  919.67    86.7  908.76    96.4  899.87     106  891.71   115.6  884.46
   125.3  879.72   134.9  877.54   144.5  876.08   154.2  874.99   163.8  874.33
   183.1  871.27   184.3  871.27   192.7  871.26   199.3  872.79   202.3  873.48
   221.6  880.98   231.2  883.09   240.9  884.21   250.5  885.59   260.2  887.72
   269.8   891.4     289  895.02   298.7  897.52   308.3  901.22   327.6  909.39
#Mann= 3 , 0 , 0
       0     .08       0   184.3    .045       0   199.3     .08       0
Bank Sta=184.3,199.3
XS Rating Curve= 0 ,0
Exp/Cntr=0.3,0.1

Type RM Length L Ch R = 1 ,12324.3 ,400.7,399.9,399.2
XS GIS Cut Line= 2
     1697106.659      272310.673     1697370.339      272244.752
#Sta/Elev= 29
       0  907.31    19.4  900.64    29.1  897.21    48.5  889.86    58.2  886.98
      68  885.36    77.7  884.53    87.4  883.18    97.1   880.6   106.8  876.96
   116.5  873.03   126.2  869.66   135.9   867.7   145.6  866.31   151.7  865.55
   155.3   865.1     165  866.43   166.7  866.99   174.7  869.61   184.4  873.01
   194.1  875.98   203.8  878.62   213.6  880.64   223.3   882.3     233  884.18
   242.7  886.55   252.4  889.29   262.1  893.59   271.8  896.96
#Mann= 3 , 0 , 0
       0     .08       0   151.7    .045       0   166.7     .08       0
Bank Sta=151.7,166.7
XS Rating Curve= 0 ,0
Exp/Cntr=0.3,0.1

Type RM Length L Ch R = 1 ,11924.3 ,391.8,399.8,407.9
XS GIS Cut Line= 2
     1697175.136      272709.581     1697514.822      272612.527
#Sta/Elev= 30
       0  900.44    19.6  885.51    29.4  878.59    39.2  873.51    49.1  871.88
    58.9  871.57    68.7  871.01    78.5     870    88.3  868.61   127.6  863.68
   137.4  862.84   147.2   862.6     157  861.56   161.3   860.7   166.8  859.61
   176.3  858.47   176.6  858.43   186.4  858.49   196.3  858.95   215.9  860.12
   225.7  860.82   235.5  862.36   245.3  863.76   274.8  867.75   294.4  870.14
   304.2  871.11     314  871.85   333.6  872.93   343.5   873.2   353.3  873.32
#Mann= 3 , 0 , 0
       0     .08       0   161.3    .045       0   176.3     .08       0
Bank Sta=161.3,176.3
XS Rating Curve= 0 ,0
Exp/Cntr=0.3,0.1

Type RM Length L Ch R = 1 ,11524.3 ,378.9,382.4,385.7
XS GIS Cut Line= 2
     1697165.122      273038.039     1697534.071      273066.419
#Sta/Elev= 30
       0  899.32     9.7  893.74    19.5  888.78    29.2  884.33    48.7  876.11
    58.4   872.3    68.2  868.77    77.9  865.66    87.6  861.93    97.4  859.28
   107.1  858.05   116.8   857.2   136.3  855.88   146.1  855.51   165.5  855.37
   175.3   854.3     185  852.43     188  852.21   194.8  851.72     203  852.98
   204.5  853.21   214.2  855.43     224  857.43   233.7   858.9   243.4  860.02
   253.2  860.86   282.4  862.84   292.1  863.62   340.8  865.53     370  867.53
#Mann= 3 , 0 , 0
       0     .08       0     188    .045       0     203     .08       0
Bank Sta=188,203
XS Rating Curve= 0 ,0
Exp/Cntr=0.3,0.1

Type RM Length L Ch R = 1 ,11141.8 ,291.4,290.7,290.2
XS GIS Cut Line= 2
     1697042.722      273360.874     1697423.839      273452.233
#Sta/Elev= 30
       0  897.02    29.4  880.94      49  870.75    58.8  863.39    68.6  859.55
    78.4   856.6    88.2  855.04   107.8  853.64     147   851.4   156.8  850.18
   166.6  850.16   176.4  850.68   186.2  850.16   204.5  845.48   205.8  845.16
   215.6  844.79   219.5  845.22   225.4  845.88   235.2   847.6   254.7  850.66
   264.5  851.78   303.7   853.7   313.5  854.29   333.1  856.02   342.9  857.08
   352.7   858.7   362.5  861.82   372.3  864.16   382.1  869.28   391.9  876.69
#Mann= 3 , 0 , 0
       0     .08       0   204.5    .045       0   219.5     .08       0
Bank Sta=204.5,219.5
XS Rating Curve= 0 ,0
Exp/Cntr=0.3,0.1

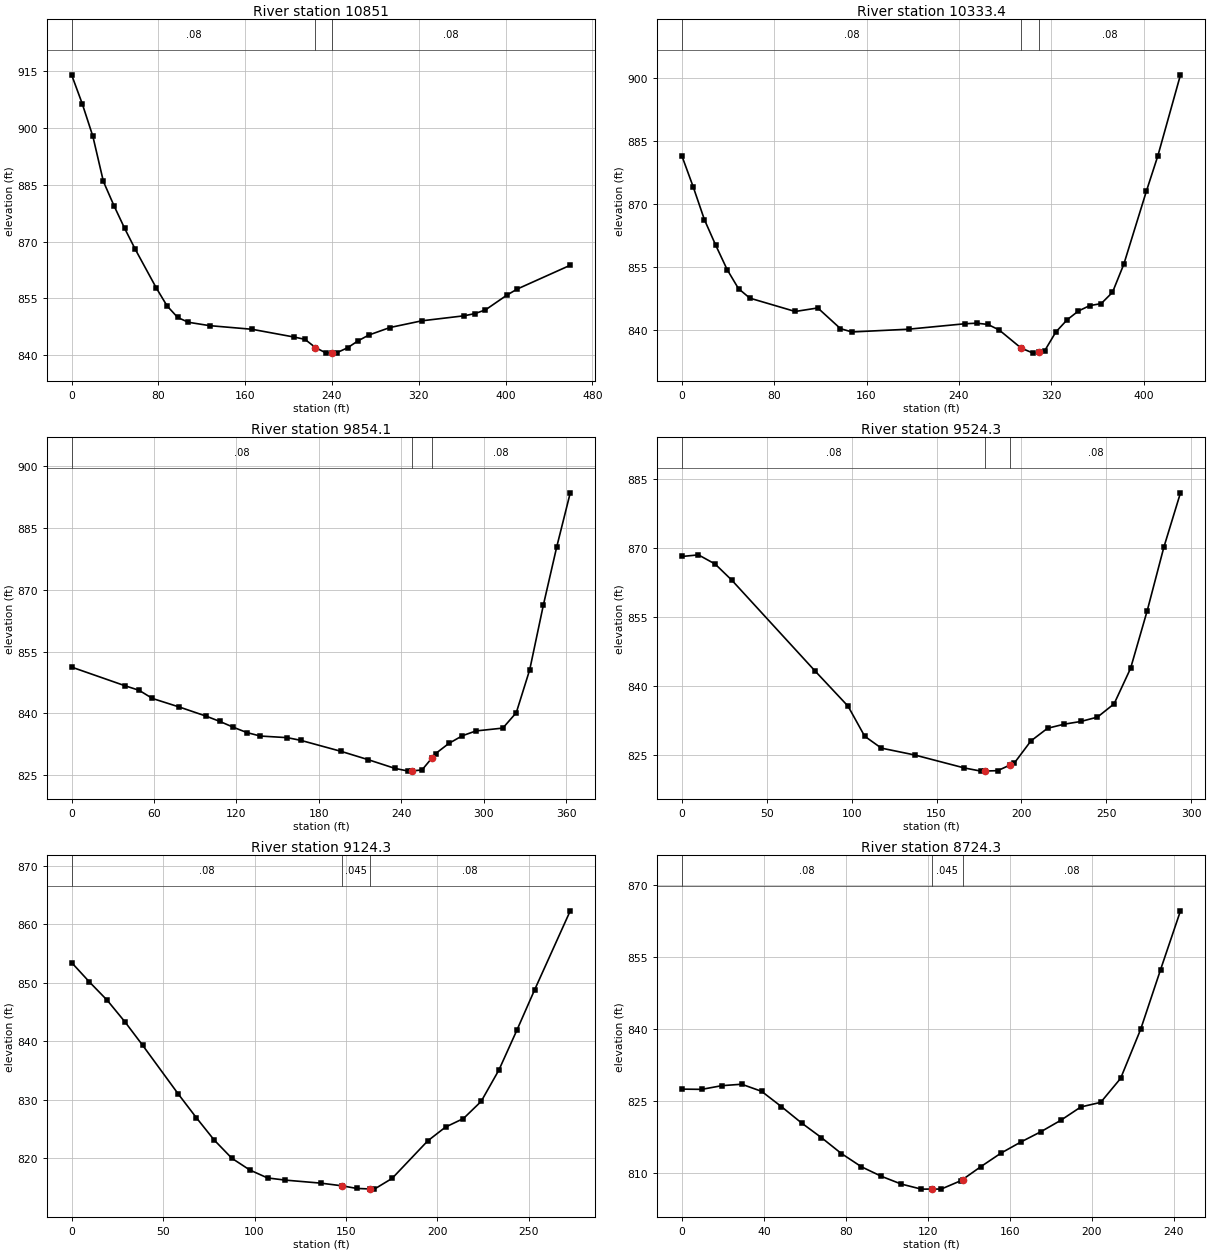
Type RM Length L Ch R = 1 ,10851   ,515.3,517.6,520
XS GIS Cut Line= 2
     1696914.522      273633.151     1697365.068      273724.033
#Sta/Elev= 30
       0  914.05     9.8  906.43    19.6  897.81    29.3  885.89    39.1  879.47
    48.9   873.5    58.7  867.97    78.2   857.7      88  853.03    97.8  849.97
   107.6  848.71   127.1  847.82   166.2  846.86   205.4  844.79   215.1   844.2
   224.7  842.04   234.7  840.56   239.7  840.62   244.5  840.68   254.3  841.96
     264   843.8   273.8  845.32   293.4  847.32   322.7  849.09   361.8  850.42
   371.6  850.99   381.4  851.97     401  855.84   410.7  857.48   459.6  863.77
#Mann= 3 , 0 , 0
       0     .08       0   224.7    .045       0   239.7     .08       0
Bank Sta=224.7,239.7
XS Rating Curve= 0 ,0
Exp/Cntr=0.3,0.1

Type RM Length L Ch R = 1 ,10333.4 ,479.7,479.1,478.4
XS GIS Cut Line= 2
     1696787.571      274096.449     1697200.695      274222.738
#Sta/Elev= 30
       0  881.48     9.8  874.11    19.6  866.23    29.4  860.14    39.3  854.34
    49.1  849.82    58.9  847.56    98.2  844.38   117.8  845.22   137.4   840.3
   147.3   839.5   196.4  840.16   245.4  841.46   255.3  841.59   265.1   841.3
   274.9  839.98     294  835.65   304.4  834.46     309  834.69   314.2  834.95
     324  839.48   333.8   842.4   343.6   844.5   353.4  845.78   363.3  846.25
   373.1  848.95   382.9  855.63   402.5  873.07   412.4  881.46     432  900.75
#Mann= 3 , 0 , 0
       0     .08       0     294    .045       0     309     .08       0
#XS Ineff= 2 , 0
          256.01  841.47
Permanent Ineff=
       F       F
Bank Sta=294,309
XS Rating Curve= 0 ,0
Exp/Cntr=0.3,0.1

Type RM Length L Ch R = 1 ,9854.1  ,335.4,329.7,324.1
XS GIS Cut Line= 2
     1696696.627      274563.143     1697046.011      274661.942
#Sta/Elev= 29
       0  851.22    39.2  846.65    49.1  845.59    58.9  843.59    78.5  841.51
    98.1  839.28   107.9  838.02   117.8  836.59   127.6  835.31   137.4  834.46
     157  834.07   166.8  833.42   196.3  830.73   215.9  828.72   235.5  826.59
   245.3  825.93   247.5  825.99   255.1   826.2   262.5  829.17     265  830.18
   274.8  832.69   284.6  834.54   294.4   835.7     314  836.39   323.8  840.14
   333.6  850.61   343.5  866.28   353.3  880.52   363.1  893.59
#Mann= 3 , 0 , 0
       0     .08       0   247.5    .045       0   262.5     .08       0
Bank Sta=247.5,262.5
XS Rating Curve= 0 ,0
Exp/Cntr=0.3,0.1

Type RM Length L Ch R = 1 ,9524.3  ,398.6,399.9,401.2
XS GIS Cut Line= 2
     1696683.927      274945.355     1696977.558      274952.322
#Sta/Elev= 25
       0  868.21     9.8  868.56    19.6  866.57    29.4  863.07    78.3  843.35
    97.9  835.62   107.7  829.08   117.5  826.49   137.1     825   166.4  822.17
   176.2  821.48   178.5   821.5     186  821.58   193.5  822.84   195.8  823.22
   205.6  828.05   215.4  830.81   225.2   831.7     235  832.29   244.8  833.24
   254.6  836.13   264.3  843.85   274.1   856.4   283.9  870.22   293.7  882.07
#Mann= 3 , 0 , 0
       0     .08       0   178.5    .045       0   193.5     .08       0
Bank Sta=178.5,193.5
XS Rating Curve= 0 ,0
Exp/Cntr=0.3,0.1

Type RM Length L Ch R = 1 ,9124.3  ,412.7,400,387.2
XS GIS Cut Line= 2
     1696636.961      275327.266     1696908.613      275349.904
#Sta/Elev= 26
       0  853.45     9.7  850.15    19.5     847    29.2  843.31    38.9   839.3
    58.4  830.97    68.2  826.96    77.9  823.17    87.6  820.04    97.4  818.04
   107.1  816.68   116.8  816.31   136.3  815.79     148  815.33   155.8  814.89
     163   814.8   165.5  814.77   175.2   816.6   194.7  823.01   204.4  825.36
   214.2  826.82   223.9  829.75   233.6  835.11   243.4  841.89   253.1  848.78
   272.6  862.28
#Mann= 3 , 0 , 0
       0     .08       0     148    .045       0     163     .08       0
Bank Sta=148,163
XS Rating Curve= 0 ,0
Exp/Cntr=0.3,0.1

Type RM Length L Ch R = 1 ,8724.3  ,406.1,400,393.9
XS GIS Cut Line= 2
     1696710.291      275793.404     1696925.746      275680.547
#Sta/Elev= 28
       0  827.46     9.7  827.41    19.5  828.18    29.2  828.48    38.9     827
    48.6   823.8    58.4   820.4    68.1  817.34    77.8  814.03    87.6  811.26
    97.3  809.28     107  807.66   116.8   806.6   121.9  806.61   126.5  806.61
   136.2  808.38   136.9  808.59   145.9  811.31   155.7  814.12   165.4  816.44
   175.1  818.57   184.8  820.95   194.6  823.74   204.3   824.7     214   829.7
   223.8  839.96   233.5   852.4   243.2  864.65
#Mann= 3 , 0 , 0
       0     .08       0   121.9    .045       0   136.9     .08       0
Bank Sta=121.9,136.9
XS Rating Curve= 0 ,0
Exp/Cntr=0.3,0.1

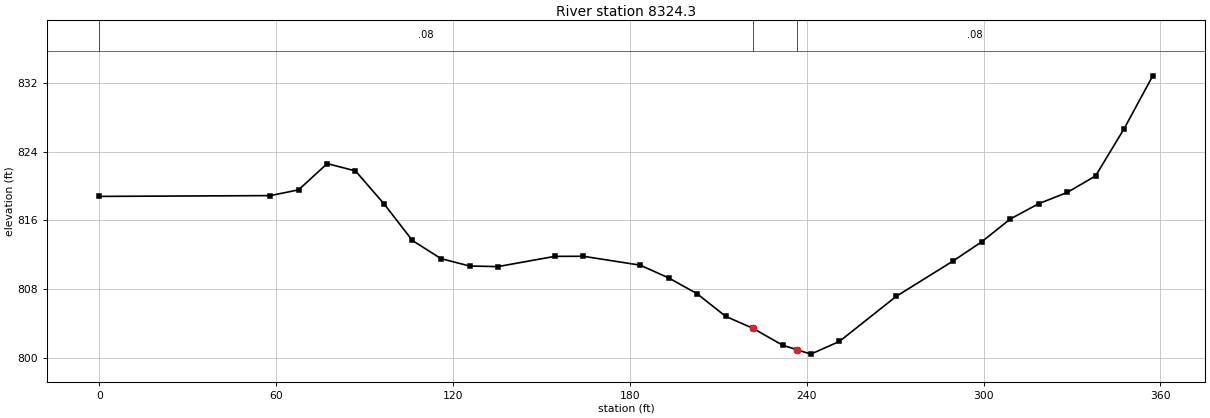
Type RM Length L Ch R = 1 ,8324.3  ,403.1,400.1,397.1
XS GIS Cut Line= 2
     1696872.327      276226.527     1697132.778      275981.862
#Sta/Elev= 30
       0   818.8      58  818.89    67.6  819.56    77.3  822.61    86.9  821.76
    96.6  817.93   106.2  813.68   115.9  811.57   125.6  810.71   135.2  810.64
   154.5  811.83   164.2  811.84   183.5  810.81   193.2  809.32   202.8  807.49
   212.5  804.86   221.7  803.48   231.8  801.51   236.7  800.98   241.4  800.47
   251.1  801.95   270.4  807.19   289.7   811.3   299.4  813.53   309.1  816.18
   318.7  817.95   328.4  819.26     338  821.18   347.7  826.67   357.4  832.81
#Mann= 3 , 0 , 0
       0     .08       0   221.7    .045       0   236.7     .08       0
Bank Sta=221.7,236.7
XS Rating Curve= 0 ,0
Exp/Cntr=0.3,0.1