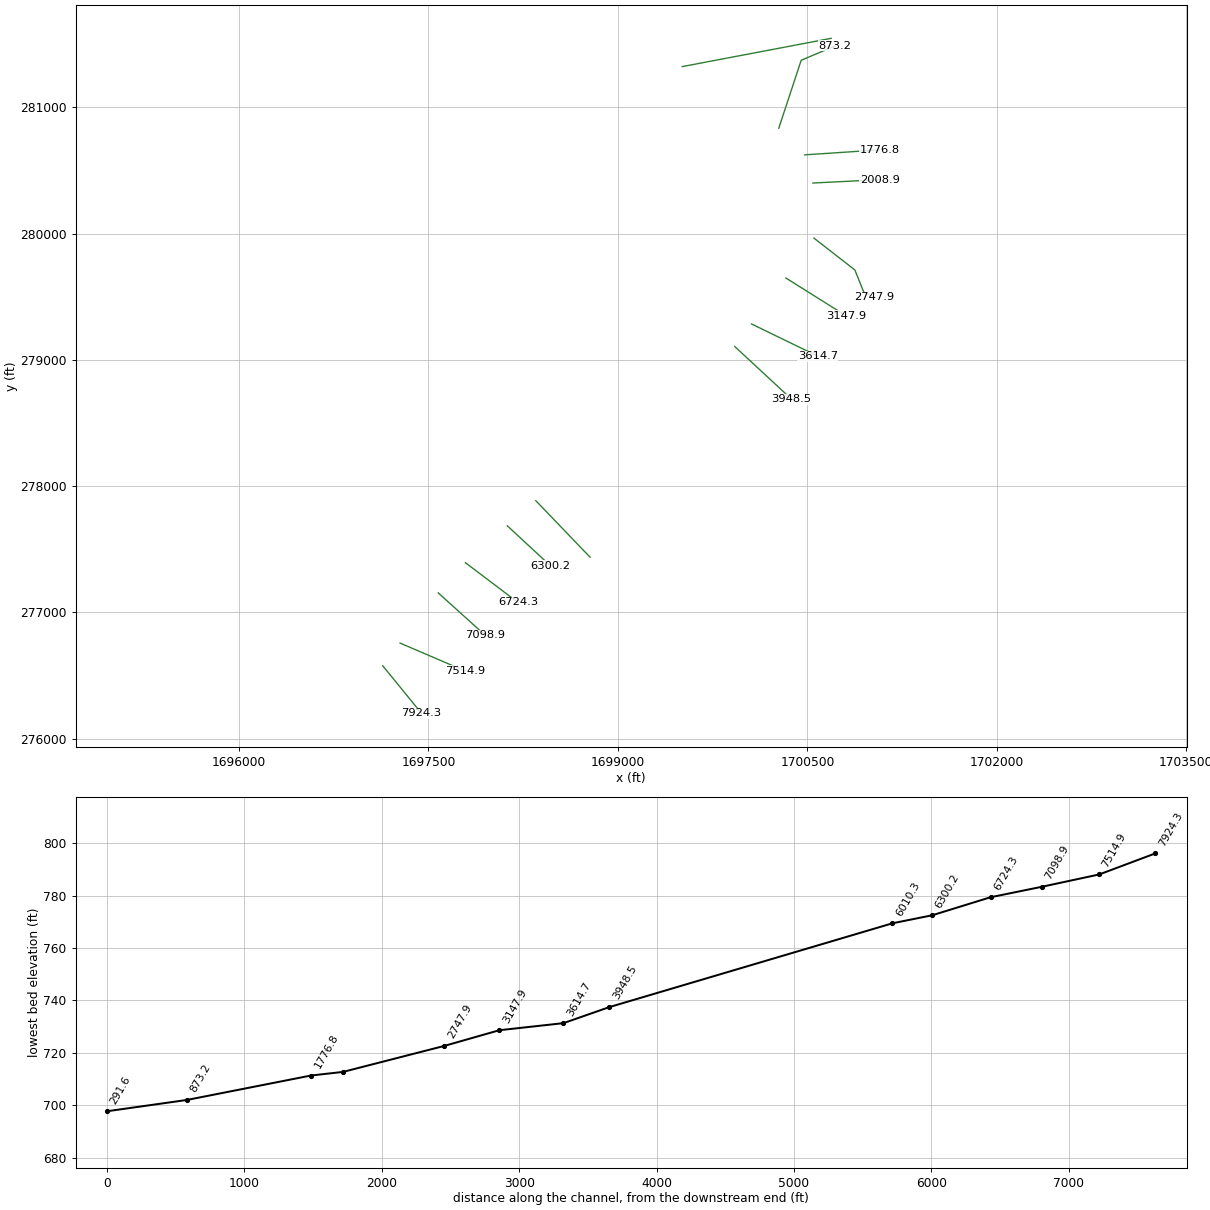
HEC-RAS study RICHCRK.prj: RICHCRK

--- RICHCRK.g01 (geometry) --- (continued)

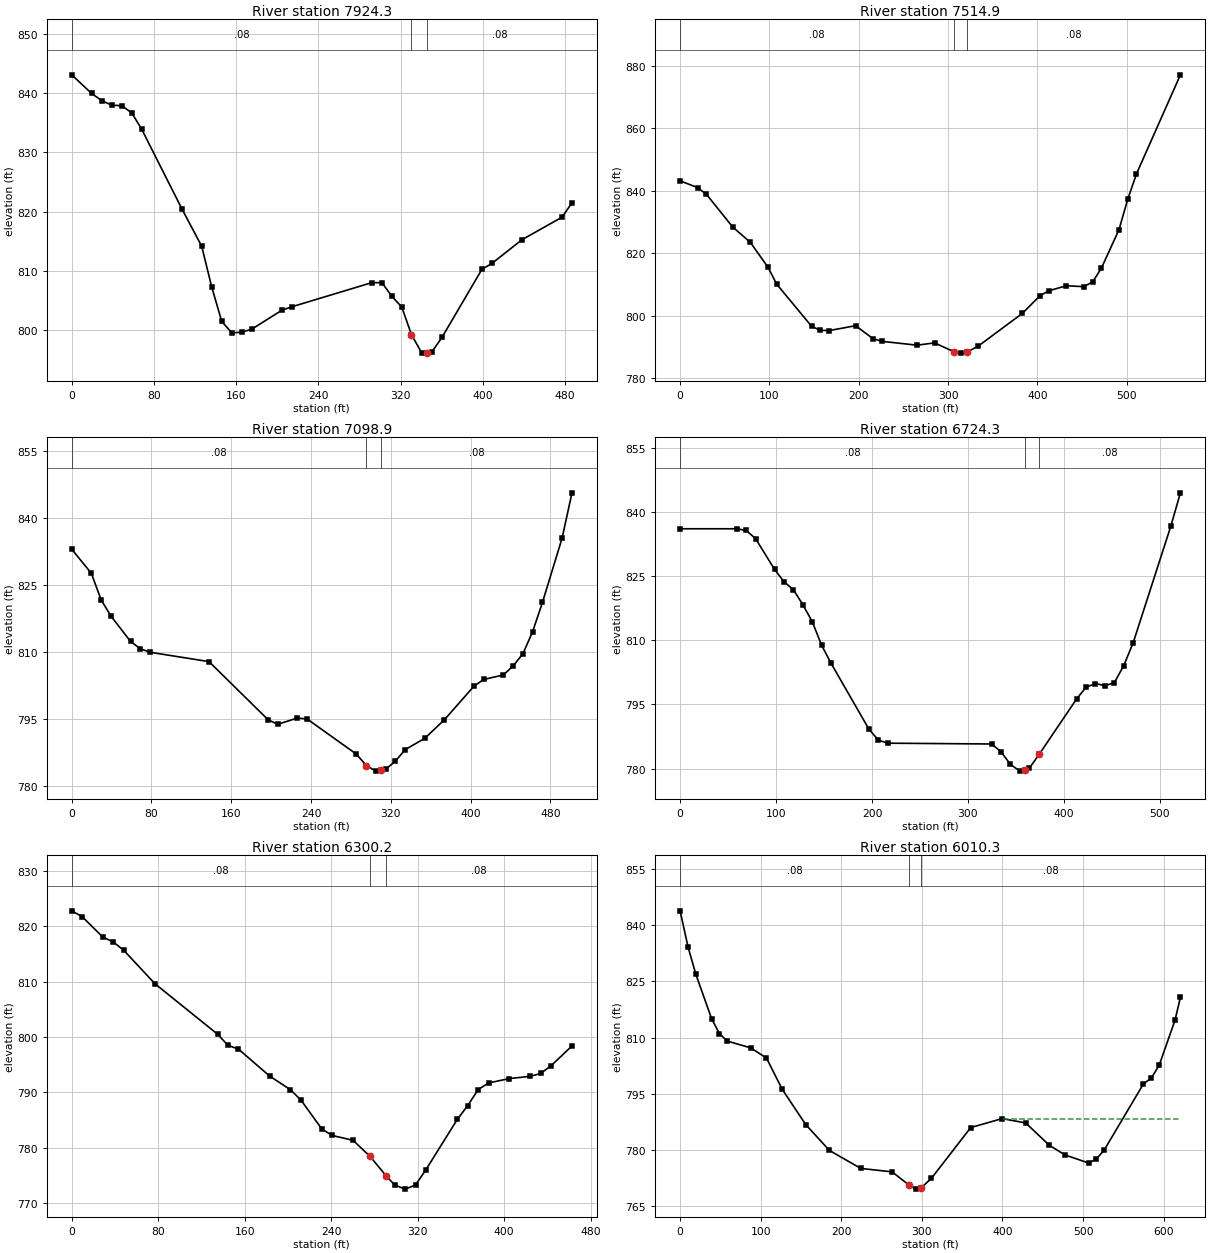
Type RM Length L Ch R = 1 ,7924.3  ,398.3,409.1,419.9
XS GIS Cut Line= 2
     1697137.565      276578.266      1697445.24      276201.147
#Sta/Elev= 30
       0  843.09    19.5  839.94    29.2  838.74    38.9  837.97    48.7  837.88
    58.4  836.68    68.1  833.91   107.1  820.52   126.5  814.16   136.3  807.25
     146  801.48   155.8  799.56   165.5  799.67   175.2  800.18   204.4  803.37
   214.2  803.96     292  808.03   301.8  808.02   311.5  805.73   321.2  803.89
   330.5  799.27   340.7  796.14   345.5  796.24   350.4  796.35   360.2  798.79
   399.1  810.28   408.8  811.27     438  815.27     477  819.07   486.7  821.51
#Mann= 3 , 0 , 0
       0     .08       0   330.5    .045       0   345.5     .08       0
#XS Ineff= 2 , 0
          302.41  807.81
Permanent Ineff=
       F       F
Bank Sta=330.5,345.5
XS Rating Curve= 0 ,0
Exp/Cntr=0.3,0.1

Type RM Length L Ch R = 1 ,7514.9  ,423.6,416.1,408.6
XS GIS Cut Line= 2
     1697274.616       276757.85     1697789.425      276537.079
#Sta/Elev= 30
       0  843.19    19.6  841.03    29.5  838.88      59  828.39    78.6  823.54
    98.3  815.61   108.1  810.18   147.4  796.62   157.2  795.39   167.1  795.32
   196.5  796.87   216.2  792.68     226  791.87   265.3  790.64     285  791.38
   306.8   788.5   314.5   788.1   321.8  788.49   334.1   790.4   383.3  800.83
   402.9  806.43   412.7  808.02   432.4  809.64     452  809.36   461.9  810.85
   471.7  815.25   491.4  827.56   501.2  837.27     511  845.41   560.2  877.09
#Mann= 3 , 0 , 0
       0     .08       0   306.8    .045       0   321.8     .08       0
Bank Sta=306.8,321.8
XS Rating Curve= 0 ,0
Exp/Cntr=0.3,0.1

Type RM Length L Ch R = 1 ,7098.9  ,372.5,374.6,376.7
XS GIS Cut Line= 2
     1697577.489      277154.718     1697949.896      276818.757
#Sta/Elev= 30
       0  833.09    19.7  827.69    29.5  821.76    39.3  818.14      59  812.44
    68.8   810.8    78.7  810.01   137.7  807.92   196.7  794.96   206.5  793.88
   226.2  795.29     236  795.09   285.2  787.25   295.5  784.65   304.9  783.41
   310.5  783.63   314.7   783.8   324.5  785.64   334.4  788.23     354  790.75
   373.7  794.91   403.2   802.4     413  803.92   432.7  804.93   442.6  806.94
   452.4  809.69   462.2  814.66     472  821.17   491.7  835.57   501.6   845.7
#Mann= 3 , 0 , 0
       0     .08       0   295.5    .045       0   310.5     .08       0
Bank Sta=295.5,310.5
XS Rating Curve= 0 ,0
Exp/Cntr=0.3,0.1

Type RM Length L Ch R = 1 ,6724.3  ,426.5,424.7,422.9
XS GIS Cut Line= 2
     1697792.255      277394.153     1698208.152      277079.706
#Sta/Elev= 30
       0  836.03      59  836.03    68.9  835.63    78.7  833.72    98.4  826.55
   108.2  823.68     118  821.81   127.9   818.3   137.7  814.32   147.6  808.77
   157.4  804.57   196.8   789.2   206.6  786.65   216.4  785.93   324.6  785.74
   334.5  783.92   344.3  780.96   354.2   779.4   359.5  779.77     364  780.08
   374.5  783.42   413.2  796.26     423  798.98   432.8  799.87   442.7  799.38
   452.5  800.04   462.4  804.08   472.2  809.41   511.6  836.77   521.4  844.43
#Mann= 3 , 0 , 0
       0     .08       0   359.5    .045       0   374.5     .08       0
Bank Sta=359.5,374.5
XS Rating Curve= 0 ,0
Exp/Cntr=0.3,0.1

Type RM Length L Ch R = 1 ,6300.2  ,291.1,289.2,287.4
XS GIS Cut Line= 2
     1698124.086      277686.164     1698463.408      277371.524
#Sta/Elev= 30
       0  822.78     9.6  821.74    28.9  818.02    38.6  817.15    48.2  815.64
    77.1   809.6     135  800.49   144.6  798.48   154.2  797.82   183.2  792.92
   202.4  790.47   212.1   788.6   231.4  783.38     241  782.21   260.3  781.33
   275.9  778.45   290.9  774.92   298.9  773.25   308.5  772.52   318.1  773.27
   327.8  776.06   356.7  785.11   366.3   787.6     376  790.49   385.6  791.69
   404.9  792.49   424.2  792.89   433.8  793.41   443.5  794.81   462.8  798.38
#Mann= 3 , 0 , 0
       0     .08       0   275.9    .045       0   290.9     .08       0
Bank Sta=275.9,290.9
XS Rating Curve= 0 ,0
Exp/Cntr=0.3,0.1

Type RM Length L Ch R = 1 ,6010.3  ,2059.6,2061.1,2062.6
XS GIS Cut Line= 3
     1698349.923      277884.901     1698775.145      277441.963
     1698779.844      277437.069
#Sta/Elev= 30
       0  843.89     9.8  834.27    19.5  826.96      39  815.09    48.7  811.07
    58.5  809.06    87.7  807.23   107.2  804.52   126.7  796.16   155.9  786.72
   185.2  779.82   224.2     775   263.2  774.07   284.1  770.53   292.4  769.46
   299.1  769.81   311.9  772.36   360.6  785.92   399.6  788.32   428.8  787.17
   458.1  781.19   477.6  778.61   506.8  776.45   516.6  777.54   526.3  779.93
     575  797.63   584.8  799.18   594.5   802.6     614  814.56   620.8  820.75
#Mann= 3 , 0 , 0
       0     .08       0   284.1    .045       0   299.1     .08       0
#XS Ineff= 2 , 0
                          400.11          788.33
Permanent Ineff=
       F       F
Bank Sta=284.1,299.1
XS Rating Curve= 0 ,0
Exp/Cntr=0.3,0.1

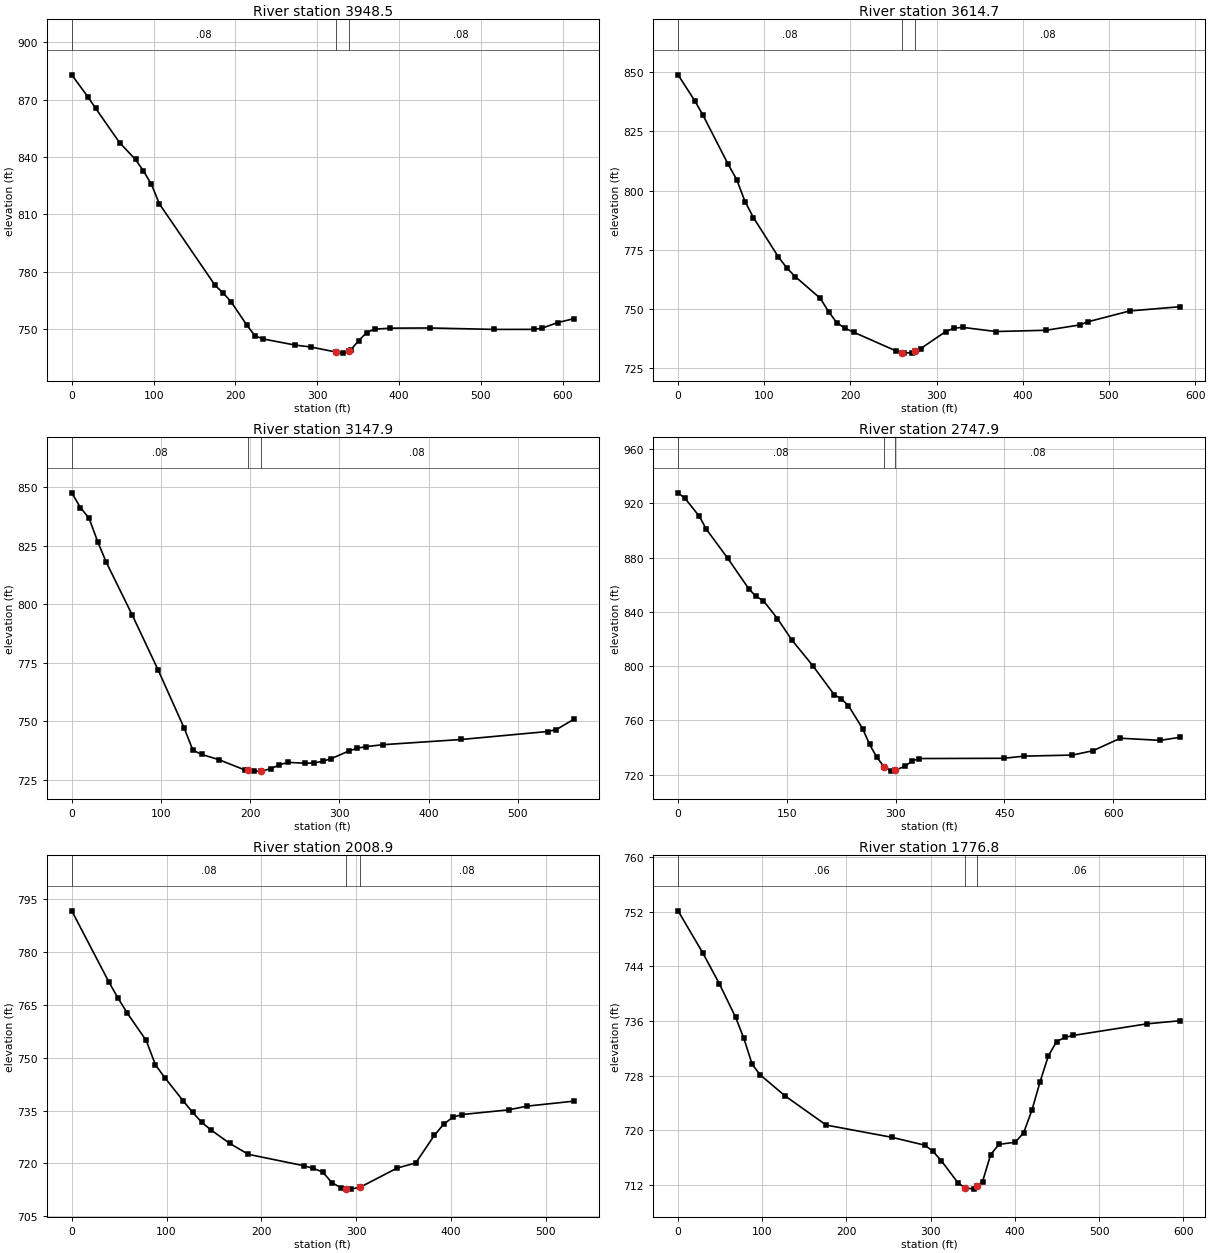
Type RM Length L Ch R = 1 ,3948.5  ,328.3,333.7,339.2
XS GIS Cut Line= 2
     1699925.048        279105.3     1700374.743      278688.114
#Sta/Elev= 30
       0  882.98    19.5  871.58    29.2  865.47    58.4  847.54    77.9  838.71
    87.6  832.74    97.4  825.67   107.1  815.49   175.3  772.83     185  768.92
   194.7   764.3   214.2  751.96   223.9   746.5   233.7  744.88   272.6   741.7
   292.1  740.67   323.2  738.01     331  737.46   338.2  738.66   340.8   739.1
   350.5  743.91   360.3  748.21     370  749.98   389.5  750.52   438.2  750.61
     516  749.86   564.7  749.88   574.5  750.48   593.9  753.44   613.4  755.44
#Mann= 3 , 0 , 0
       0     .08       0   323.2    .045       0   338.2     .08       0
Bank Sta=323.2,338.2
XS Rating Curve= 0 ,0
Exp/Cntr=0.3,0.1

Type RM Length L Ch R = 1 ,3614.7  ,468,466.7,465.2
XS GIS Cut Line= 2
     1700057.685      279284.115     1700581.593       279029.58
#Sta/Elev= 30
       0  848.88    19.4  837.91    29.1  831.71    58.2  811.03      68  804.67
    77.7  795.36    87.4  788.62   116.5  771.93   126.2  767.32   135.9  763.68
     165   754.5   174.7  748.86   184.4  744.09   194.2   741.8   203.9  740.16
   252.4  732.36   260.4  731.52   262.1  731.34   271.8  731.58   275.4   732.2
   281.5  733.25   310.6  740.46   320.4  741.88   330.1  742.23   368.9  740.46
   427.1     741     466  743.24   475.7  744.59   524.2  749.16   582.5  750.94
#Mann= 3 , 0 , 0
       0     .08       0   260.4    .045       0   275.4     .08       0
Bank Sta=260.4,275.4
XS Rating Curve= 0 ,0
Exp/Cntr=0.3,0.1

Type RM Length L Ch R = 1 ,3147.9  ,400.1,399.8,399.5
XS GIS Cut Line= 2
     1700329.619      279647.919     1700806.301       279348.69
#Sta/Elev= 30
       0  847.61     9.7  841.31    19.4  836.74    29.1  826.69    38.8  817.83
    67.9  795.31      97  771.75   126.2  746.91   135.8   737.6   145.6  735.78
     165  733.54   194.1  729.12   197.1  728.97   203.8  728.64   212.1  728.67
   223.2  729.64   232.9  731.37   242.6  732.38     262  732.01   271.7  732.13
   281.4  732.85   291.1     734   310.5  737.23   320.2  738.44   329.9  739.12
   349.3  739.95   436.7  742.17   533.7  745.58   543.4   746.4   562.8  750.77
#Mann= 3 , 0 , 0
       0     .08       0   197.1    .045       0   212.1     .08       0
Bank Sta=197.1,212.1
XS Rating Curve= 0 ,0
Exp/Cntr=0.3,0.1

Type RM Length L Ch R = 1 ,2747.9  ,724.8,738.8,752.9
XS GIS Cut Line= 4
     1700551.479      279964.008     1700875.734      279711.646
     1700946.451      279535.566      1701029.11      279496.612
#Sta/Elev= 30
       0  927.76     9.8  923.58    29.4  910.36    39.1  900.82    68.5  879.52
    97.8  856.79   107.6  851.37   117.4  848.38     137  835.07   156.5  819.57
   185.9  800.24   215.2  779.02     225  775.93   234.8  771.01   254.4  753.97
   264.1  742.32   273.9  732.96   284.1   725.8   293.5  722.66   299.1  723.14
   313.1  726.39   322.8  730.13   332.6  731.94   448.8  732.12   477.3  733.72
   543.7  734.49   572.2  737.73   609.8  746.91   664.6  745.33     692  747.58
#Mann= 3 , 0 , 0
       0     .08       0   284.1    .045       0   299.1     .08       0
Bank Sta=284.1,299.1
XS Rating Curve= 0 ,0
Exp/Cntr=0.3,0.1

Type RM Length L Ch R = 1 ,2008.9  ,231.6,232,232.3
XS GIS Cut Line= 2
     1700543.784      280400.051      1701072.72       280426.23
#Sta/Elev= 30
       0   791.7    39.2  771.49      49  766.84    58.8  762.58    78.5  754.92
    88.3  747.99    98.1  744.38   117.7  737.72   127.5   734.5   137.3  731.64
   147.1  729.48   166.7  725.69   186.3   722.6   245.2  719.34     255   718.6
   264.8  717.56   274.6  714.52   284.4  713.07   289.5  712.89   294.2  712.72
   304.5  713.29   343.2  718.69   362.9  720.15   382.5  727.96   392.3  731.12
   402.1  733.13   411.9  733.89   460.9  735.22   480.6  736.28   529.6  737.68
#Mann= 3 , 0 , 0
       0     .08       0   289.5    .045       0   304.5     .08       0
Bank Sta=289.5,304.5
XS Rating Curve= 0 ,0
Exp/Cntr=0.3,0.1

Type RM Length L Ch R = 1 ,1776.8  ,876.2,903.4,930.7
XS GIS Cut Line= 2
     1700477.955      280622.857      1701072.72      280662.558
#Sta/Elev= 30
       0  752.14    29.3  745.98    48.9  741.48    68.4  736.52    78.2  733.43
      88  729.63    97.7  728.08     127  725.02   175.9  720.74   254.1  718.94
   293.2  717.78   302.9  716.87   312.7   715.5   332.2  712.31   340.6  711.54
   351.8  711.35   355.6  711.78   361.6  712.46   371.3  716.42   381.1  717.91
   400.6  718.23   410.4  719.62   420.2   722.9     430  727.12   439.7  730.86
   449.5  732.98   459.3  733.58     469  733.87     557  735.58   596.1  736.03
#Mann= 3 , 0 , 0
       0     .06       0   340.6    .045       0   355.6     .06       0
Bank Sta=340.6,355.6
XS Rating Curve= 0 ,0
Exp/Cntr=0.3,0.1

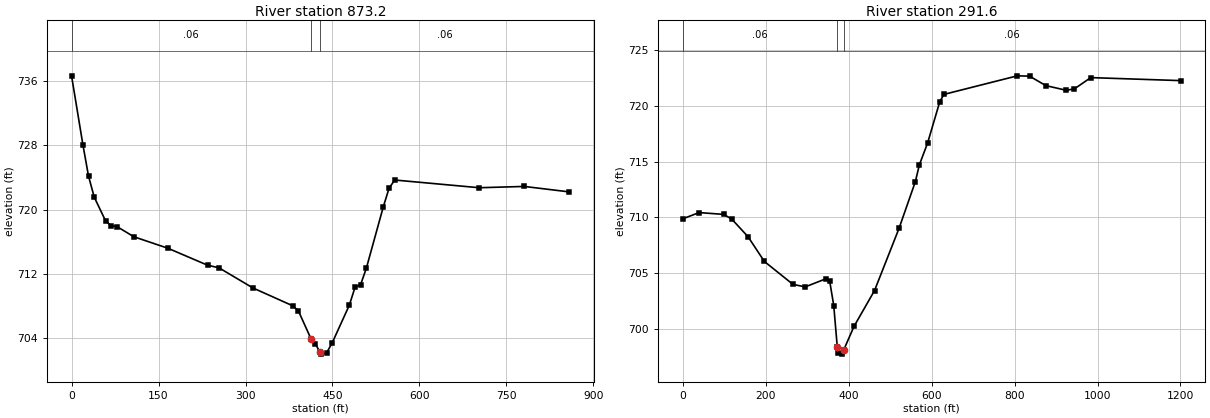
Type RM Length L Ch R = 1 ,873.2   ,605.6,581.2,556.9
XS GIS Cut Line= 3
     1700273.129      280833.302     1700450.702       281371.73
     1700719.066      281485.411
#Sta/Elev= 30
       0  736.64    19.6  728.05    29.3  724.15    39.1  721.55    58.6  718.61
    68.4  717.98    78.2  717.89   107.5  716.62   166.2  715.19   234.6  713.08
   254.2  712.76   312.8  710.25   381.2  708.04     391  707.43   412.8  703.94
   420.3  703.34   427.8  702.33   430.1  702.02   439.9  702.19   449.6  703.44
     479  708.11   488.8  710.32   498.5  710.67   508.3  712.69   537.6  720.34
   547.4  722.63   557.2  723.68     703  722.72   780.7  722.88   858.4   722.2
#Mann= 3 , 0 , 0
       0     .06       0   412.8    .045       0   427.8     .06       0
Bank Sta=412.8,427.8
XS Rating Curve= 0 ,0
Exp/Cntr=0.3,0.1

Type RM Length L Ch R = 1 ,291.6   ,295,291.5,287.9
XS GIS Cut Line= 2
     1699509.185      281321.726     1700688.228      281545.465
#Sta/Elev= 30
       0  709.87    39.4  710.43    98.4  710.27     118  709.85   157.4  708.26
   196.7  706.04   265.6  703.98   295.1  703.75   344.3  704.47   354.1  704.31
     364  702.08   372.6  698.32   373.8   697.8   383.6  697.71   387.6  698.05
   413.1  700.22   462.3  703.42   521.4  709.01   560.7   713.2   570.5  714.73
   590.2  716.67   619.7   720.4   629.6  721.05   806.6  722.72   836.1  722.69
   875.5  721.84   924.7  721.42   944.3  721.55   983.7  722.56  1200.1  722.29
#Mann= 3 , 0 , 0
       0     .06       0   372.6    .045       0   387.6     .06       0
Bank Sta=372.6,387.6
XS Rating Curve= 0 ,0
Exp/Cntr=0.3,0.1

Chan Stop Cuts=-1
Use User Specified Reach Order=0
Composite Channel Slope=5